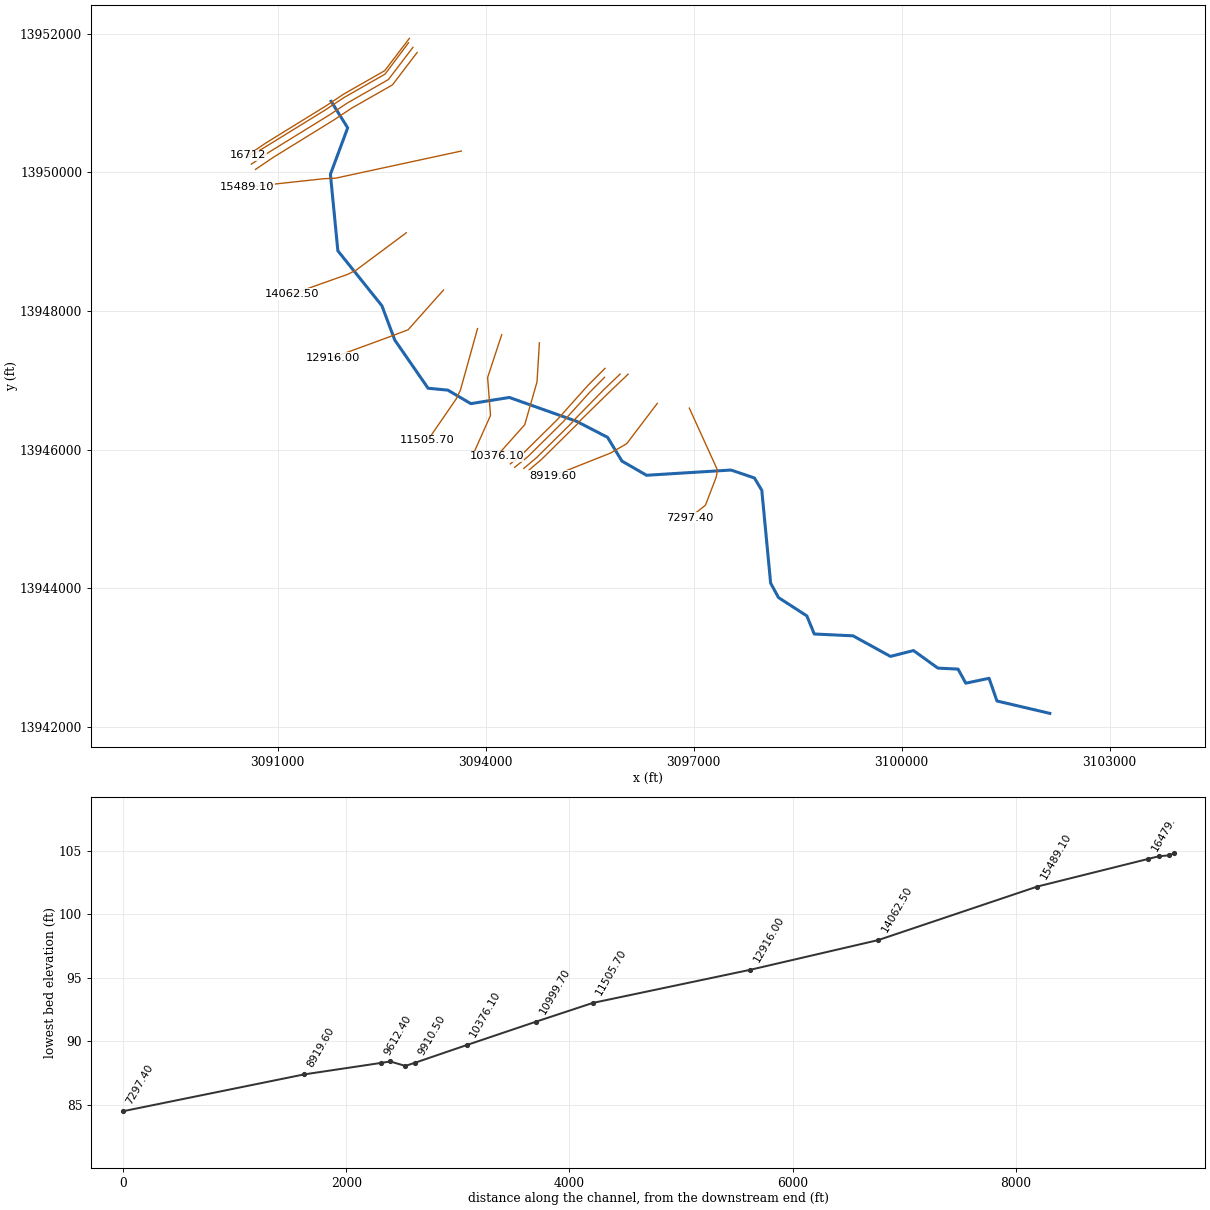
--- K120-01-00.prj (project) ---

Proj Title=K120-01-00
Current Plan=p07
Default Exp/Contr=.3,.1
English Units
Geom File=g03
Flow File=f02
Flow File=f01
Plan File=p07
Plan File=p06
Y Axis Title=Elevation
X Axis Title(PF)=Main Channel Distance
X Axis Title(XS)=Station
BEGIN DESCRIPTION:
Cypress Creek Watershed
Senger Gully
HCFCD Unit K120-01-00
Flood Hazard Model
10, 2, 1, 0.2%
Filename K120-01-00
Prepared by:  Halff Associates Inc  DATE:  03-26-04
Reviewed by:  _________  DATE:  __________________
STATUS (Final)
Appeal Revised
END DESCRIPTION:
DSS Export Rating Curves= 0
DSS Export Rating Curve Sorted= 0
DSS Export Volume Flow Curves= 0
DXF OffsetX= 0
DXF OffsetY= 0
DXF ScaleX= 1
DXF ScaleY= 10

--- K120-01-00.p07 (plan) ---

Plan Title=Floodway
Version=Version 3.0.1  Mar 2001
Short Identifier=Floodway0607
Geom File=g03
Flow File=f02
Subcritical Flow
K Sum by GR= 0
Std Step Tol= 0.01
Critical Tol= 0.01
Num of Std Step Trials= 20
Max Error Tol= 0.3
Flow Tol Ratio= 0.001
Split Flow NTrial= 30
Split Flow Tol= 0.02
Split Flow Ratio= 0.02
Log Output Level= 0
Friction Slope Method= 1
Unsteady Friction Slope Method= 2
Parabolic Critical Depth
Global Vel Dist= 0 , 0 , 0
Global Log Level= 0
CheckData=True
Encroach Param=-1 ,0,0, 2
Encroach River=K120-01-00
Encroach Reach=Reach - 1
Encroach Node=16712
       1    4930    5065
Encroach Node=16667.80
       1    4930    5065
Encroach Node=16621.20
       1    4500    5700
Encroach Node=16574.60
       1    4900    5065
Encroach Node=16479.
       1    4860    5125
Encroach Node=15489.10
       1 4825.07 5134.53
Encroach Node=14062.50
       1    4910    5090
Encroach Node=12916.00
       1    4844    5031
Encroach Node=11505.70
       1    4865    5037
Encroach Node=10999.70
       1    4930    5034
Encroach Node=10376.10
       1    4940    5070
Encroach Node=9910.50
       1    4900    5100
Encroach Node=9827.60
       1    4850    5150
Encroach Node=9759.35
       1    4850    5150
Encroach Node=9691.10
       1    4900    5100
Encroach Node=9612.40
       1 4911.39 5073.97
Encroach Node=8919.60
       1 4894.79    5011
Encroach Node=7297.40
       1  4946.2  5043.5
Encroach Node=7262.80
       1    4915    5085
Encroach Node=7253.15
       1    4915    5085
Encroach Node=7243.50
       1  4958.1  5039.9
Encroach Node=7235.70
       1  4958.2  5039.9
Encroach Node=7039.85
       1  4958.2  5039.9
Encroach Node=6844.00
       1  4958.2  5039.9
Encroach Node=6740.
       1  4931.7  5060.4
Encroach Node=6170.80
       1  4972.2  5027.9
Encroach Node=5571.70
       1    4972  5027.8
Encroach Node=5102.30
       1  4972.2  5029.1
Encroach Node=4878.
       1  4952.6  5052.6
Encroach Node=4780.00
       1    4964  5035.3
Encroach Node=4775.75
       1    4964  5035.3
Encroach Node=4771.50
       1    4964  5035.3
Encroach Node=4765.30
       1    4964  5035.4
Encroach Node=4737.50
       1    4964  5035.4
Encroach Node=4709.70
       1    4964  5035.4
Encroach Node=4614.
       1  4945.2  5055.2
Encroach Node=4277.70
       1  4973.1  5027.3
Encroach Node=3485.90
       1  4968.6  5021.5
Encroach Node=2768.80
       1    4944  5034.7
Encroach Node=1072.60
       1  4955.6  5020.8
Encroach Reach=K120-01-00_0011
Encroach Node=16712
       1    4930    5065
Encroach Node=16667.80
       1    4930    5065
Encroach Node=16621.20
       1    4500    5700
Encroach Node=16574.60
       1    4900    5065
Encroach Node=16479.
       1    4860    5125
Encroach Node=15489.10
       1 4825.07 5134.53
Encroach Node=14062.50
       1    4910    5090
Encroach Node=12916.00
       1    4844    5031
Encroach Node=11505.70
       1    4865    5037
Encroach Node=10999.70
       1    4930    5034
Encroach Node=10376.10
       1    4940    5070
Encroach Node=9910.50
       1    4900    5100
Encroach Node=9827.60
       1    4850    5150
Encroach Node=9759.35
       1    4850    5150
Encroach Node=9691.10
       1    4900    5100
Encroach Node=9612.40
       1 4911.39 5073.97
Encroach Node=8919.60
       1 4894.79    5011
Encroach Node=7297.40
       1  4946.2  5043.5
Encroach Node=7262.80
       1    4915    5085
Encroach Node=7253.15
       1    4915    5085
Encroach Node=7243.50
       1  4958.1  5039.9
Encroach Node=7235.70
       1  4958.2  5039.9
Encroach Node=7039.85
       1  4958.2  5039.9
Encroach Node=6844.00
       1  4958.2  5039.9
Encroach Node=6740.
       1  4931.7  5060.4
Encroach Node=6170.80
       1  4972.2  5027.9
Encroach Node=5571.70
       1    4972  5027.8
Encroach Node=5102.30
       1  4972.2  5029.1
Encroach Node=4878.
       1  4952.6  5052.6
Encroach Node=4780.00
       1    4964  5035.3
Encroach Node=4775.75
       1    4964  5035.3
Encroach Node=4771.50
       1    4964  5035.3
Encroach Node=4765.30
       1    4964  5035.4
Encroach Node=4737.50
       1    4964  5035.4
Encroach Node=4709.70
       1    4964  5035.4
Encroach Node=4614.
       1  4945.2  5055.2
Encroach Node=4277.70
       1  4973.1  5027.3
Encroach Node=3485.90
       1  4968.6  5021.5
Encroach Node=2768.80
       1    4944  5034.7
Encroach Node=1072.60
       1  4955.6  5020.8
BEGIN DESCRIPTION:
Appeal Revised
END DESCRIPTION:
Computation Interval=1HOUR
Output Interval=1HOUR
Run HTab= 0
Run UNet= 0
Run PostProcess= 0
UNET Theta= 1
UNET ZTol= 0.02
UNET ZSATol= 0.1
UNET MxIter= 20
UNET MaxInSteps= 20
UNET DtIC= 0
UNET DtMin= 0
UNET MaxCRTS= 20
UNET WFStab= 2
UNET SFStab= 1
UNET WFX= 1
UNET SFX= 1
UNET Convert EG Bridges=-1
UNET Use Existing IB Tables=-1
Instantaneous Interval=1HOUR
Write IC File= 0
Write Velocity= 0
Write Detailed= 0

--- K120-01-00.p06 (plan) ---

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Plan Title=FEMA Effective June 2007
Short Identifier=FEMAeff0607
Geom File=g03
Flow File=f01
UNET ZSATol= 0.05
UNET MaxInSteps= 0
IC Time=0

--- K120-01-00.f02 (steady flow) ---

Flow Title=Floodway
Version=Version 3.0.1  Mar 2001
Number of Profiles= 2
Profile Names=1PCT_100yr, 1PCTFloodway_100yrFW
River Rch & RM=K120-01-00,K120-01-00_0011,16712
    1580    1580
River Rch & RM=K120-01-00,K120-01-00_0011,15489.10
    1670    1670
River Rch & RM=K120-01-00,K120-01-00_0011,14062.50
    1750    1750
River Rch & RM=K120-01-00,K120-01-00_0011,12916.00
    1860    1860
River Rch & RM=K120-01-00,K120-01-00_0011,11505.7
    1990    1990
River Rch & RM=K120-01-00,K120-01-00_0011,9827.60
    2000    2000
River Rch & RM=K120-01-00,K120-01-00_0011,9691.10
    2080    2080
River Rch & RM=K120-01-00,K120-01-00_0011,8919.60
    2250    2250
River Rch & RM=K120-01-00,K120-01-00_0011,7262.80
    2300    2300
River Rch & RM=K120-01-00,K120-01-00_0011,6844.00
    2380    2380
River Rch & RM=K120-01-00,K120-01-00_0011,4709.70
    2460    2460
River Rch & RM=K120-01-00,K120-01-00_0011,2768.80
    2520    2520
River Rch & RM=K120-01-00,K120-01-00_0011,1072.6
    2567    2567
Boundary for River Rch & Prof#=K120-01-00,K120-01-00_0011, 1
Up Type= 0
Dn Type= 3
Dn Slope=.0013
Boundary for River Rch & Prof#=K120-01-00,K120-01-00_0011, 2
Up Type= 0
Dn Type= 1
Dn Known WS=83.98
DSS Import GetInterval= 0
DSS Import GetPeak= 0
DSS Import FillOption= 0

--- K120-01-00.f01 (steady flow) ---

Flow Title=FEMA Effective June 2007
Version=Version 3.0.1  Mar 2001
Number of Profiles= 4
Profile Names=10PCT_10yr, 2PCT_50yr, 1PCT_100yr, 0.2PCT_500yr
River Rch & RM=K120-01-00,K120-01-00_0011,16712
     800    1280    1580    2040
River Rch & RM=K120-01-00,K120-01-00_0011,15489.10
     870    1380    1670    2230
River Rch & RM=K120-01-00,K120-01-00_0011,14062.50
     920    1470    1750    2390
River Rch & RM=K120-01-00,K120-01-00_0011,12916.00
    1000    1590    1860    2600
River Rch & RM=K120-01-00,K120-01-00_0011,11505.70
    1090    1740    1990    2870
River Rch & RM=K120-01-00,K120-01-00_0011,9827.60
    1100    1750    2000    2900
River Rch & RM=K120-01-00,K120-01-00_0011,9691.10
    1150    1790    2080    2990
River Rch & RM=K120-01-00,K120-01-00_0011,8919.60
    1270    1880    2250    3190
River Rch & RM=K120-01-00,K120-01-00_0011,7262.80
    1300    1900    2300    3250
River Rch & RM=K120-01-00,K120-01-00_0011,6844.00
    1330    1980    2380    3390
River Rch & RM=K120-01-00,K120-01-00_0011,4709.70
    1360    2060    2460    3520
River Rch & RM=K120-01-00,K120-01-00_0011,2768.80
    1390    2130    2520    3630
River Rch & RM=K120-01-00,K120-01-00_0011,1072.60
    1402    2175    2567    3710
Boundary for River Rch & Prof#=K120-01-00,K120-01-00_0011, 1
Up Type= 0
Dn Type= 3
Dn Slope=.0013
Boundary for River Rch & Prof#=K120-01-00,K120-01-00_0011, 2
Up Type= 0
Dn Type= 3
Dn Slope=.0013
Boundary for River Rch & Prof#=K120-01-00,K120-01-00_0011, 3
Up Type= 0
Dn Type= 3
Dn Slope=.0013
Boundary for River Rch & Prof#=K120-01-00,K120-01-00_0011, 4
Up Type= 0
Dn Type= 3
Dn Slope=.0013
DSS Import GetInterval= 0
DSS Import GetPeak= 0
DSS Import FillOption= 0

--- K120-01-00.g03 (geometry) ---

Geom Title=K120-01-00 June 2007
Version=Version 3.0.1  Mar 2001

River Reach=K120-01-00      ,K120-01-00_0011
Reach XY= 30
      3091772.21     13951025.48      3092010.54      13950643.2
       3091761.4     13949973.06      3091869.04     13948869.76
      3092504.46     13948077.23      3092689.36      13947583.3
        3093170.       13946888.      3093454.11     13946861.08
      3093786.58     13946665.77      3094341.26     13946755.18
       3095313.5       13946410.       3095758.8     13946179.66
       3095965.4     13945837.64      3096320.43     13945632.78
      3097539.18      13945708.3        3097876.       13945594.
      3097982.76     13945416.64      3098110.35     13944076.59
      3098224.08     13943868.89      3098632.13       13943605.
       3098739.7     13943343.72      3099298.68     13943317.38
      3099837.79      13943020.8      3100170.26       13943105.
      3100522.69     13942851.53      3100812.62     13942837.64
       3100924.6     13942634.52      3101260.54     13942704.83
      3101374.25     13942377.57      3102136.48       13942199.

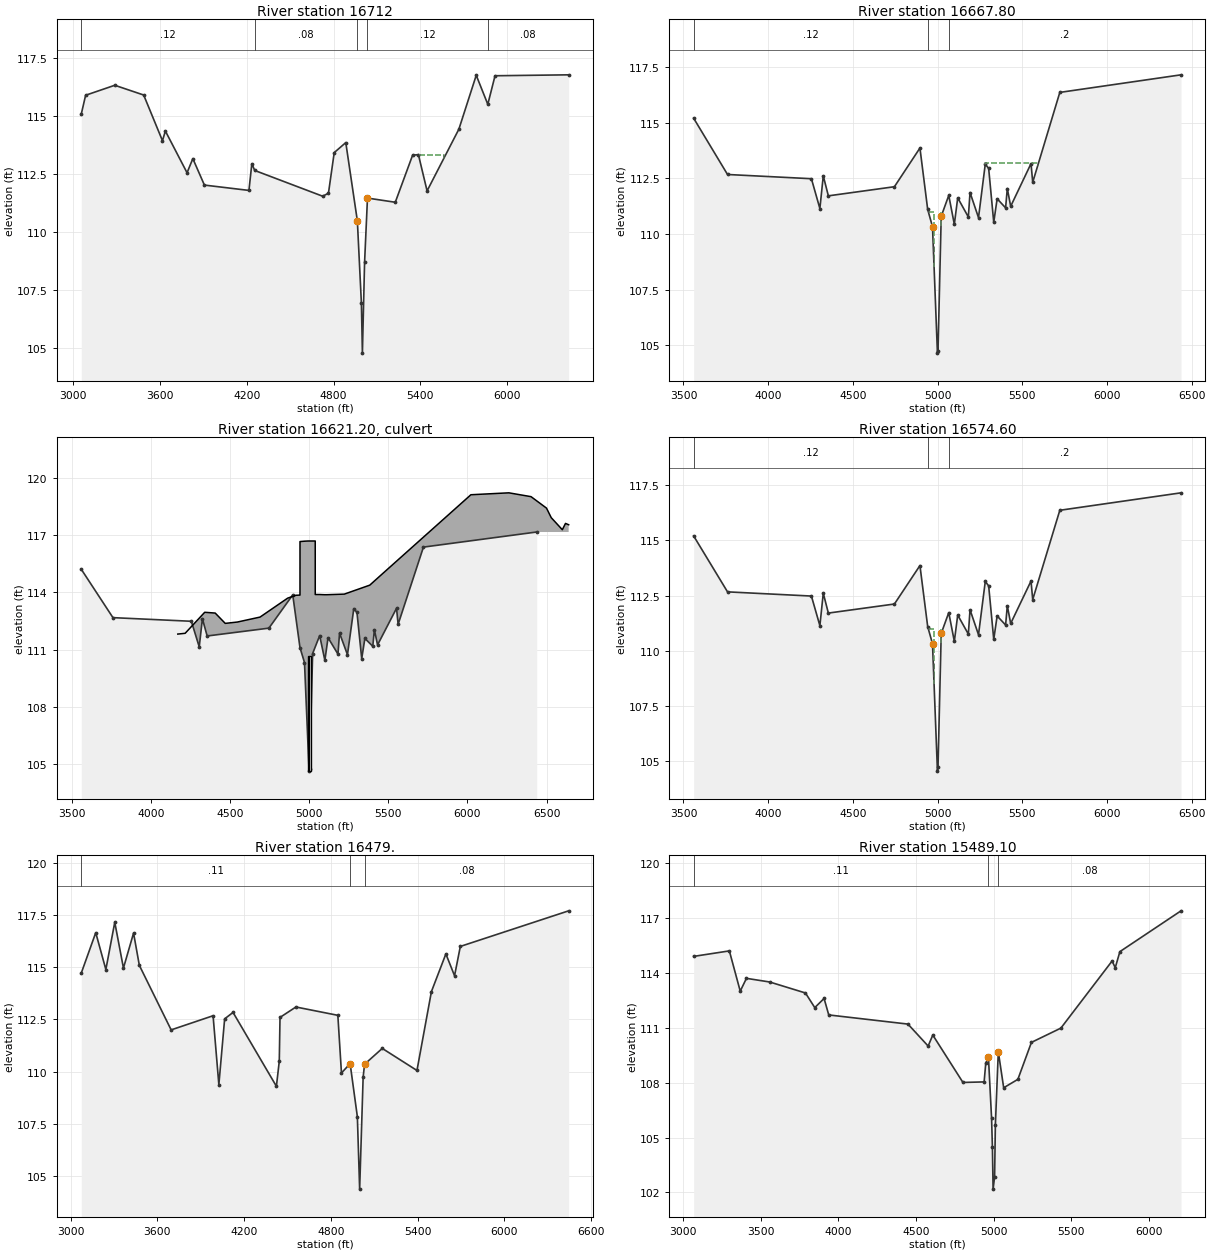
Type RM Length L Ch R = 1 ,16712   ,44,44.2,45
BEGIN DESCRIPTION:
Louetta Rd - XS 4
END DESCRIPTION:
XS GIS Cut Line= 6
       3092900.6     13951934.17      3092545.03     13951467.67
      3091954.48     13951130.77      3091694.44     13950957.83
      3090824.93     13950421.57       3090570.2     13950248.91
#Sta/Elev= 30
    3055  115.09    3085   115.9  3286.6  116.33  3486.6  115.91  3616.6  113.94
  3636.6  114.36  3786.6  112.56  3826.6  113.17  3906.6  112.03  4214.7   111.8
  4234.7  112.95  4254.7  112.66  4724.7  111.55  4764.7  111.68  4804.6  113.43
  4884.6  113.86  4964.6  110.49  4992.6  106.93  4999.5  104.79  5014.6   108.7
  5034.6  111.47  5226.9  111.29  5346.9  113.32  5386.9  113.34  5446.9  111.78
  5666.9  114.44  5786.9  116.76  5866.9  115.51  5916.9  116.74  6426.2  116.78
#Mann= 5 ,-1 , 0
    3055     .12       0  4254.7     .08       0  4964.6     .04       0
  5034.6     .12       0  5866.9     .08       0
#XS Ineff= 2 ,-1
 3733.37 4835.15  112.65 5387.79 5561.57  113.32
Permanent Ineff=
       F       F
Bank Sta=4964.6,5034.6
XS Rating Curve= 0
Exp/Cntr=.5,.3

Type RM Length L Ch R = 1 ,16667.80,93.2,93.2,93.2
BEGIN DESCRIPTION:
Louetta Rd - XS 3
Upstream Section of Bridge/Culvert/Weir
END DESCRIPTION:
XS GIS Cut Line= 6
  3092888.61967613951870.8463336      3092549.93     13951418.39
      3091956.02     13951079.57      3091695.68     13950906.44
       3090831.3     13950373.33 3090573.551727213950219.8613231
#Sta/Elev= 30
  3560.3   115.2  3760.3  112.67  4255.5  112.48  4305.5  111.14  4325.5  112.61
  4355.5  111.71  4745.5  112.12  4896.2  113.86  4941.9   111.1  4970.4  110.32
  4999.5  104.64  5002.8  104.73  5021.8  110.79  5066.3  111.73  5099.2  110.43
  5119.2  111.62  5181.9  110.76  5191.9  111.86  5241.9  110.73  5281.9  113.14
  5301.9  112.94  5331.9  110.52  5351.9  111.58  5401.9  111.17  5411.9  112.04
  5431.9  111.24  5551.9  113.16  5561.9  112.32  5721.9  116.36  6437.4  117.15
#Mann= 3 ,-1 , 0
  3560.3     .12       0  4941.9     .04       0  5066.3      .2       0
#XS Ineff= 4 ,-1
 3717.48 4903.18  112.42  4945.6  4979.6     111  5020.4  5031.7     111
 5281.53 5591.36  113.19
Permanent Ineff=
       F       F       F       F
Bank Sta=4970.4,5021.8
XS Rating Curve= 0
Exp/Cntr=.5,.3

Type RM Length L Ch R = 2 ,16621.20,,,
BEGIN DESCRIPTION:
LOUETTA ROAD
Structure ID: K120-01-00-S6
END DESCRIPTION:
Bridge Culvert--1,0,-1,-1, 0
Deck Dist Width WeirC Skew NumUp NumDn MinLoCord MaxHiCord MaxSubmerge Is_Ogee
10,74,3,0, 36, 36, , , .95, 0, 0,0,,
    4170  4216.3    4340  4406.3  4469.7  4546.3  4689.7    4864  4916.1  4941.9
    4942  4970.4  4992.6  4996.9  4999.5  5002.8  5004.3  5007.2  5021.8  5038.3
 5038.41    5046  5066.3  5095.9  5111.5  5221.6  5382.7  5452.7  6021.6  6261.6
  6401.6  6499.3  6529.3  6599.3  6619.3  6639.3
  111.81  111.85  112.95  112.91  112.37  112.44   112.7  113.69  113.84  113.85
  116.65  116.67  116.68  116.68  116.68  116.68  116.68  116.68  116.68  116.68
  113.88  113.88  113.88  113.87  113.87   113.9  114.37  114.89   119.1   119.2
     119   118.4   117.9  117.27   117.6  117.53
     111     111     111     111     111     111     111     111     111  110.66
  110.66  109.88  105.34  104.33  103.92  104.29  104.88  105.58  110.35   110.7
   110.7  110.86     111  110.48  110.06  110.08  110.08     111     111     111
     111     111     111     111     111     111
    4170  4216.3    4340  4406.3  4469.7  4546.3  4689.7    4864  4916.1  4941.9
    4942  4970.4  4992.6  4996.9  4999.5  5002.8  5004.3  5007.2  5021.8  5038.3
 5038.41    5046  5066.3  5095.9  5111.5  5221.6  5382.7  5452.7  6021.6  6261.6
  6401.6  6499.3  6529.3  6599.3  6619.3  6639.3
  111.81  111.85  112.95  112.91  112.37  112.44   112.7  113.69  113.84  113.85
  116.65  116.67  116.68  116.68  116.68  116.68  116.68  116.68  116.68  116.68
  113.88  113.88  113.88  113.87  113.87   113.9  114.37  114.89   119.1   119.2
     119   118.4   117.9  117.27   117.6  117.53
     111     111     111     111     111     111     111     111     111  110.66
  110.66  109.88  105.34  104.33  103.92  104.29  104.88  105.58  110.35   110.7
   110.7  110.86     111  110.48  110.06  110.08  110.08     111     111     111
     111     111     111     111     111     111
BR Coef= 1 , 0 , 0 ,1.25, 0 ,,,.8,-1,2,0,
WSPro=,,,, 1 ,,,, 0 ,,,, 0 ,,,,-1 ,-1 ,-1 , 0 , 0 , 0 , 0 , 0
Culvert=2,6,10,74,.015,.5,1,8,2,104.64,4994.6,104.56,4994.6,Culvert #1  , 0 ,10
Culvert Bottom n=.015
Culvert=2,6,10,74,.015,.5,1,8,2,104.64,5005.4,104.56,5005.4,Culvert #2  , 0 ,10
Culvert Bottom n=.015
BC Design=,, 0 ,, 0 ,,,,,,
BC HTab HWMax=122.64

Type RM Length L Ch R = 1 ,16574.60,96,95.6,95
BEGIN DESCRIPTION:
Louetta Rd - XS 2
Downstream Section of Bridge/Culvert/Weir
END DESCRIPTION:
XS GIS Cut Line= 6
 3092952.134473413951805.0810679      3092596.57     13951338.59
      3092006.02     13951001.69      3091745.97     13950828.75
      3090876.47     13950292.48 3090621.734124413950119.8230366
#Sta/Elev= 30
  3560.3   115.2  3760.3  112.67  4255.5  112.48  4305.5  111.14  4325.5  112.61
  4355.5  111.71  4745.5  112.12  4896.2  113.86  4941.9   111.1  4970.4  110.32
  4999.5  104.56  5002.8  104.73  5021.8  110.79  5066.3  111.73  5099.2  110.43
  5119.2  111.62  5181.9  110.76  5191.9  111.86  5241.9  110.73  5281.9  113.14
  5301.9  112.94  5331.9  110.52  5351.9  111.58  5401.9  111.17  5411.9  112.04
  5431.9  111.24  5551.9  113.16  5561.9  112.32  5721.9  116.36  6437.4  117.15
#Mann= 3 ,-1 , 0
  3560.3     .12       0  4941.9     .04       0  5066.3      .2       0
#XS Ineff= 4 ,-1
 3690.67 4897.22   112.7  4945.6  4979.6     111  5020.4  5031.7     111
 5290.47 5549.65  112.64
Permanent Ineff=
       F       F       F       F
Bank Sta=4970.4,5021.8
XS Rating Curve= 0
Exp/Cntr=.5,.3

Type RM Length L Ch R = 1 ,16479.  ,1250,989.9,858
BEGIN DESCRIPTION:
Louetta Rd - XS 1
Interpolated channel - LIDAR overbanks
END DESCRIPTION:
XS GIS Cut Line= 6
      3093011.81      13951729.5      3092656.24       13951263.
      3092065.69      13950926.1      3091805.64     13950753.16
      3090936.14      13950216.9      3090681.41     13950044.24
#Sta/Elev= 30
  3073.7  114.73  3173.7  116.67  3243.7   114.9  3305.3  117.17  3365.3  114.97
  3435.3  116.65  3475.3   115.1  3695.3     112  3985.3  112.68  4025.3  109.37
  4065.3  112.53  4123.4  112.84  4423.4  109.29  4443.3   110.5  4448.3   112.6
  4558.3   113.1  4848.3   112.7  4873.3  109.93  4933.3  110.38  4983.3  107.83
 4999.18  104.35  5023.3  109.73  5033.3  110.35  5155.6  111.11  5395.6  110.05
  5495.6  113.84  5595.6  115.65  5655.6   114.6  5695.6  116.01  6444.9  117.72
#Mann= 3 ,-1 , 0
  3073.7     .11       0  4933.3     .04       0  5033.3     .08       0
#XS Ineff= 1 ,-1
 3813.31 4682.22  111.24
Permanent Ineff=
       F
Bank Sta=4933.3,5033.3
XS Rating Curve= 0
Exp/Cntr=.3,.1

Type RM Length L Ch R = 1 ,15489.10,1401.35,1426.6,1473.88
BEGIN DESCRIPTION:
Cross Section K120-01-00-X12
END DESCRIPTION:
XS GIS Cut Line= 4
 3093648.886119713950308.8297309      3091836.05     13949917.44
      3091665.74      13949909.7      3090558.66     13949788.99
#Sta/Elev= 30
  3067.6   114.9  3297.6   115.2  3367.6     113  3407.6   113.7  3557.6   113.5
  3787.6   112.9  3847.6   112.1  3907.6   112.6  3937.6   111.7  4447.6   111.2
  4577.6     110  4607.6   110.6  4801.8  108.01  4938.1  108.04  4948.7  109.07
    4966  109.38  4986.1  106.05  4991.5  104.46  4995.9  102.18  5005.6  102.86
  5010.6  105.69  5029.4  109.69  5064.1  107.72  5155.4  108.18  5242.7   110.2
  5432.4  110.98  5762.4  114.65  5782.4  114.28  5812.4  115.16    6206  117.39
#Mann= 3 ,-1 , 0
  3067.6     .11       0    4966     .05       0  5029.4     .08       0
Bank Sta=4966,5029.4
XS Rating Curve= 0
Exp/Cntr=.3,.1

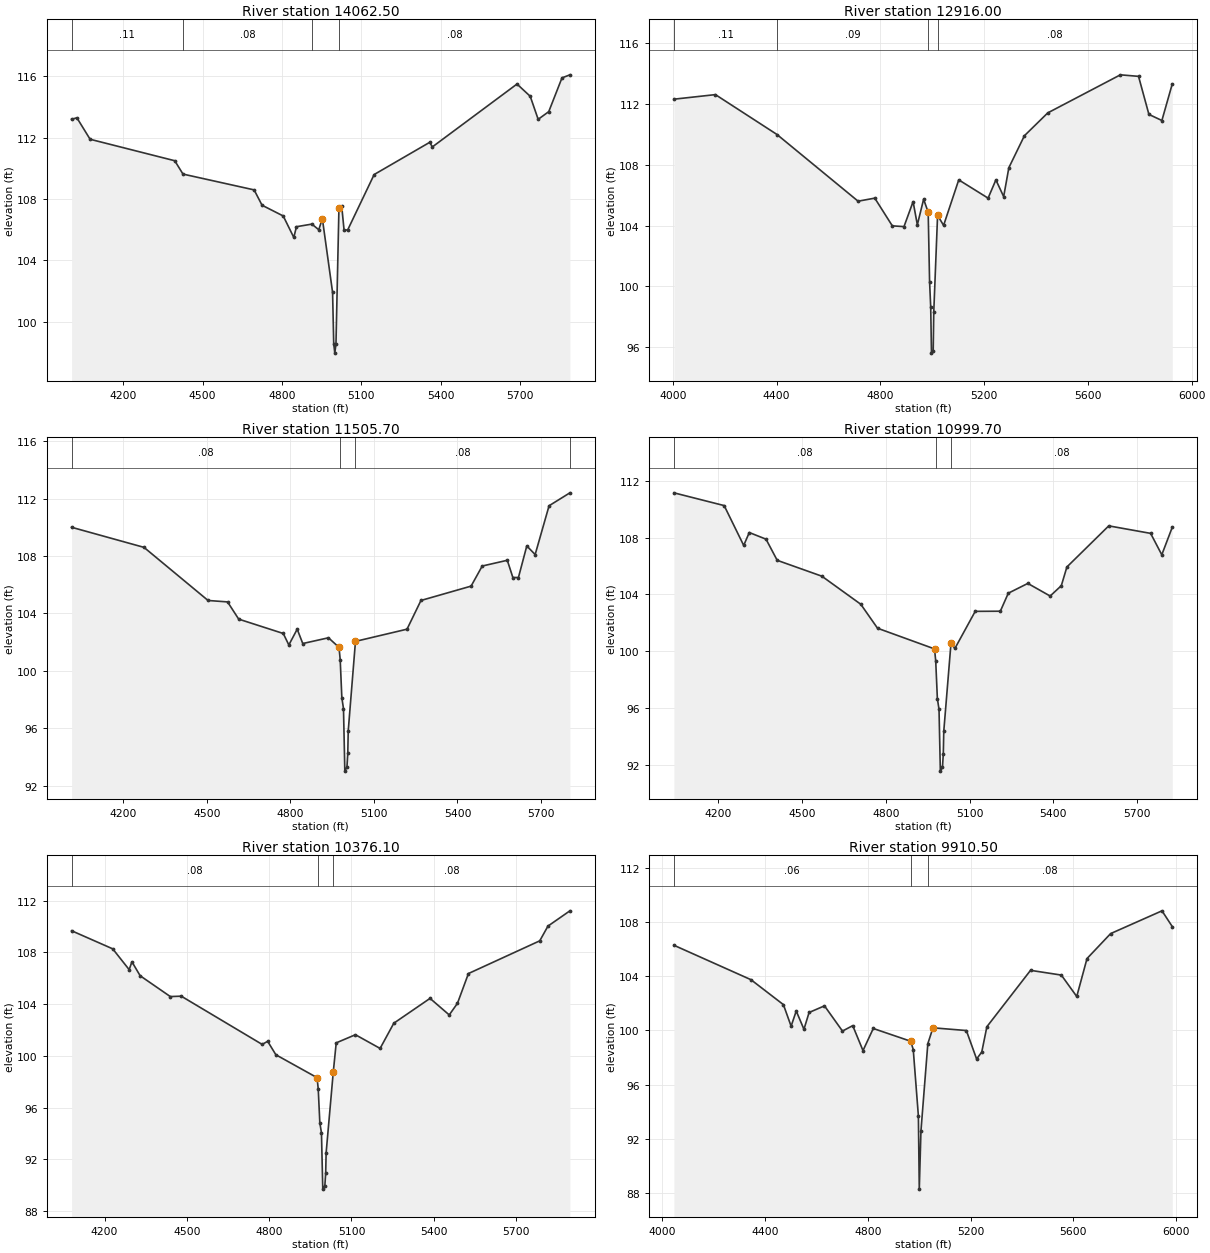
Type RM Length L Ch R = 1 ,14062.50,1146.5,1146.5,1103.4
BEGIN DESCRIPTION:
Cross Section K120-01-00-X11
END DESCRIPTION:
XS GIS Cut Line= 4
 3092855.214152413949129.6416907      3092130.21     13948589.81
       3092014.1     13948531.75 3091213.067252513948247.4336793
#Sta/Elev= 30
  4004.8   113.2  4024.8   113.3  4074.8   111.9  4394.8   110.5  4425.9  109.63
  4694.8   108.6  4724.8   107.6  4804.8   106.9  4844.8   105.5  4854.8   106.2
  4913.2  106.37  4939.2     106  4952.7  106.73  4991.4  101.92  4995.7   98.57
  4999.8   97.96  5004.2   98.57  5015.4   107.4    5026  107.52  5034.8  105.98
  5048.5  105.99  5148.5   109.6  5358.5   111.7  5368.5   111.4  5688.5   115.5
  5738.5   114.7  5768.5   113.2  5808.5   113.7  5858.5   115.9  5888.5   116.1
#Mann= 4 ,-1 , 0
  4004.8     .11       0  4425.9     .08       0  4913.2     .07       0
  5015.4     .08       0
Bank Sta=4952.7,5015.4
XS Rating Curve= 0
Exp/Cntr=.3,.1

Type RM Length L Ch R = 1 ,12916.00,1244.3,1410.3,1436
BEGIN DESCRIPTION:
Cross Section K120-01-00-X10
END DESCRIPTION:
XS GIS Cut Line= 4
 3093392.024790113948304.1195875      3092881.12     13947730.53
      3092522.36     13947596.07 3091799.394496313947331.0999985
#Sta/Elev= 30
  4003.9   112.3  4163.9   112.6  4401.3  109.98  4713.9   105.6  4778.3   105.8
  4845.9  103.98  4890.9  103.93    4926  105.57  4942.4  104.05  4966.6  105.73
  4984.2  104.87  4989.6   100.3  4993.9   98.65  4996.9   95.62  5003.5   95.76
  5005.7   98.32  5020.4  104.67  5043.6  104.01    5102     107  5215.2   105.8
  5245.2     107  5275.2   105.9  5295.2   107.8  5355.2   109.9  5445.2   111.4
  5725.2   113.9  5795.2   113.8  5835.2   111.3  5885.2   110.9  5925.2   113.3
#Mann= 4 ,-1 , 0
  4003.9     .11       0  4401.3     .09       0  4984.2     .08       0
  5020.4     .08       0
Bank Sta=4984.2,5020.4
XS Rating Curve= 0
Exp/Cntr=.3,.1

Type RM Length L Ch R = 1 ,11505.70,505,506,506
BEGIN DESCRIPTION:
Cross Section K120-01-00-X9
END DESCRIPTION:
XS GIS Cut Line= 4
 3093883.252397813947748.1665869      3093635.89     13946859.64
      3093573.96     13946731.91      3093163.28     13946134.62
#Sta/Elev= 30
  4014.5     110  4274.5   108.6  4504.5   104.9  4574.5   104.8  4614.5   103.6
  4774.5   102.6  4794.5   101.8  4824.5   102.9  4844.5   101.9  4936.8   102.3
  4974.7  101.63  4978.9  100.77  4984.8   98.12  4990.7   97.37  4995.5   93.01
  5003.1   93.29  5006.1   94.24  5007.7   95.81  5033.7  102.05  5218.8   102.9
  5268.8   104.9  5448.8   105.9  5488.8   107.3  5578.8   107.7  5598.8   106.5
  5618.8   106.5  5648.8   108.7  5678.8   108.1  5728.8   111.5  5803.6   112.4
#Mann= 4 ,-1 , 0
  4014.5     .08       0  4978.9     .06       0  5033.7     .08       0
  5803.6      .2       0
Bank Sta=4974.7,5033.7
XS Rating Curve= 0
Exp/Cntr=.3,.1

Type RM Length L Ch R = 1 ,10999.70,623.6,623.6,623
BEGIN DESCRIPTION:
Cross Section K120-01-00-X9a
Interpolated XS
END DESCRIPTION:
XS GIS Cut Line= 4
 3094231.708818213947659.7985235      3094028.66     13947042.84
      3094070.33     13946495.97      3093830.74     13945959.51
#Sta/Elev= 30
  4040.9  111.17  4220.9  110.27  4290.9  107.46  4310.9  108.37  4370.9   107.9
  4410.9  106.41  4570.9  105.29  4710.4  103.31  4770.4  101.62  4974.7  100.16
  4978.9    99.3  4984.8   96.65  4990.7    95.9  4995.5   91.54  5003.1   91.82
  5006.1   92.77  5007.7   94.34  5033.7  100.58  5047.5  100.19  5120.4  102.81
  5210.4  102.82  5238.9  104.09  5308.9  104.78  5388.9  103.89  5428.9  104.62
  5448.9  105.94  5598.9  108.84  5748.9  108.31  5788.9   106.8  5826.4  108.74
#Mann= 3 ,-1 , 0
  4040.9     .08       0  4978.9     .06       0  5033.7     .08       0
Bank Sta=4974.7,5033.7
XS Rating Curve= 0
Exp/Cntr=.3,.1

Type RM Length L Ch R = 1 ,10376.10,465,465.6,465.6
BEGIN DESCRIPTION:
Cross Section K120-01-00-X9b
Interpolated XS
END DESCRIPTION:
XS GIS Cut Line= 4
 3094775.392480513947542.9055549       3094740.9     13946979.04
      3094563.82     13946361.85 3094158.051896313945906.4538524
#Sta/Elev= 30
  4079.6  109.67  4229.6  108.27  4289.6  106.66  4299.6  107.27  4329.6  106.19
  4439.6  104.58  4479.6  104.61  4774.5  100.88  4794.5  101.12  4824.5  100.08
  4974.7   98.31  4978.9   97.45  4984.8    94.8  4990.7   94.05  4995.5   89.69
  5003.1   89.97  5006.1   90.92  5007.7   92.49  5033.7   98.73  5044.5     101
  5114.5  101.63  5204.5  100.57  5254.5  102.52  5386.6  104.44  5456.6  103.16
  5486.6  104.06  5526.6  106.36  5786.6  108.89  5816.6  110.03  5896.6  111.21
#Mann= 3 ,-1 , 0
  4079.6     .08       0  4978.9     .06       0  5033.7     .08       0
Bank Sta=4974.7,5033.7
XS Rating Curve= 0
Exp/Cntr=.3,.1

Type RM Length L Ch R = 1 ,9910.50 ,82.9,82.9,82
BEGIN DESCRIPTION:
CYPRESSWOOD DRIVE - XS 4
Interpolated XS
END DESCRIPTION:
XS GIS Cut Line= 6
 3095720.759033513947174.4090335      3095475.81     13946929.46
       3095098.5     13946507.98      3095048.18     13946449.92
      3094541.68     13945949.58 3094356.344734613945797.0601362
#Sta/Elev= 30
  4044.9  106.28  4344.9  103.74  4471.3   101.9  4501.3  100.31  4521.3  101.43
  4551.3  100.08  4571.3  101.32  4631.3  101.81  4701.3   99.95  4741.3  100.35
  4781.3   98.51  4821.3  100.14    4967    99.2    4977   98.59    4997   93.69
  5000.5   88.29    5007   92.58  5033.8   99.02  5053.8  100.19  5183.8   99.99
  5223.8   97.89  5243.8    98.4  5263.8  100.27  5433.8  104.43  5553.8  104.08
  5613.8   102.5  5653.8   105.3  5745.8  107.14  5945.8  108.82  5985.8  107.66
#Mann= 3 ,-1 , 0
  4044.9     .06       0    4967    .035       0  5033.8     .08       0
#XS Ineff= 2 , 0
       0 4951.17   98.44 5042.86       0   98.74
Permanent Ineff=
       F       F
Bank Sta=4967,5053.8
XS Rating Curve= 0
Exp/Cntr=.5,.3

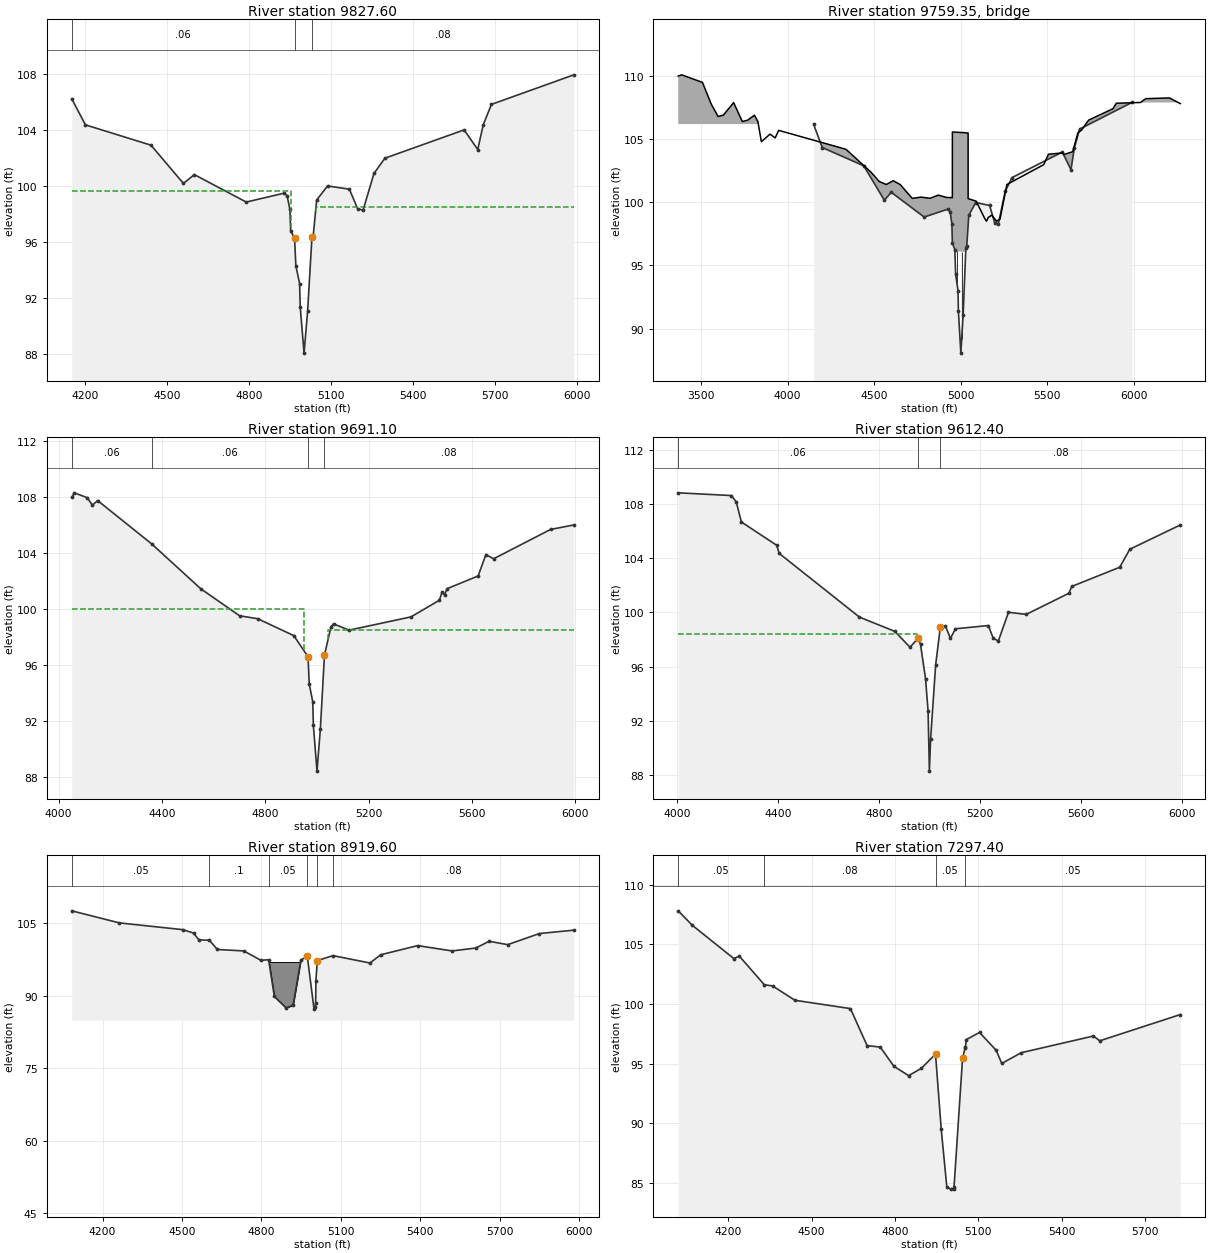
Type RM Length L Ch R = 1 ,9827.60 ,136.5,136.5,136.5
BEGIN DESCRIPTION:
CYPRESSWOOD DRIVE - XS 3
Upstream Section of Bridge/Culvert/Weir
Channel roughness value changed from 0.04 to 0.02 due to the position of the surveyed cross section falling within the limits of the concrete approach  channel.  - JJA 3/28/03
END DESCRIPTION:
XS GIS Cut Line= 6
 3095715.656377613947046.5416697       3095498.6     13946826.93
      3095169.06     13946462.97      3095118.74     13946404.91
      3094612.24     13945904.57 3094418.370574513945746.8180239
#Sta/Elev= 30
  4149.9   106.2  4199.9  104.34  4439.9  102.89  4558.7  100.16  4598.7  100.79
  4788.7   98.83  4928.7   99.47  4938.7   99.26  4948.7    98.3 4951.49   96.78
  4965.8   96.24  4970.5   94.28  4984.2   93.01  4986.4   91.36  5000.5   88.05
  5013.6   91.06  5029.4   96.34  5034.5    96.5  5046.5   98.97  5086.5   99.98
  5166.5   99.75  5196.5   98.36  5216.5   98.25  5256.5  100.87  5296.5  101.96
  5586.5  103.98  5636.5  102.58  5656.5  104.33  5686.5   105.8  5988.4  107.91
#Mann= 3 ,-1 , 0
  4149.9     .06       0  4965.8     .02       0  5029.4     .08       0
#XS Ineff= 2 , 0
       0 4951.17    99.6 5042.86       0    98.5
Permanent Ineff=
       F       F
Bank Sta=4965.8,5029.4
XS Rating Curve= 0
Exp/Cntr=.5,.3

Type RM Length L Ch R = 3 ,9759.35 ,,,
BEGIN DESCRIPTION:
CYPRESSWOOD DRIVE - inverse slope per field survey data.
Structure ID: K120-01-00-S3
END DESCRIPTION:
Bridge Culvert--1,0,-1,-1, 0
Deck Dist Width WeirC Skew NumUp NumDn MinLoCord MaxHiCord MaxSubmerge Is_Ogee
10,116,2.6,0, 60, 60, , , .95, 0, 0,0,,
  3368.3  3388.3  3508.3  3558.3  3598.3  3628.3  3688.3  3738.3  3768.3  3808.3
  3828.3  3848.3  3898.3  3928.3  3948.3  4337.1  4479.9  4529.9  4569.9  4609.9
  4649.9  4719.9  4769.9  4822.9  4870.2  4918.5 4951.49  4951.6 4951.71  4961.8
  4965.8 4966.93    4967 5026.89    5027  5029.4  5042.5 5042.61  5089.1  5138.9
  5148.9  5158.9  5178.9  5206.5  5226.5  5266.5  5478.9  5506.5  5586.5  5598.9
  5646.5  5676.5  5698.9  5738.4  5878.4  5898.9  6038.4  6068.4  6205.1    6268
     110   110.1   109.5   107.8   106.8   106.9   107.9   106.4   106.5   106.9
   106.4   104.8   105.4   105.1   105.7   104.2  102.41  101.64  101.41  101.71
  101.41  100.31  100.41  100.32  100.57  100.38  100.37  105.57  105.57  105.56
  105.56  105.56  105.56  105.51  105.51   105.5  105.49  100.29  100.09    98.7
    98.5    98.8   98.98   98.51   98.66  101.41  102.98  103.81  103.91   103.8
  104.01  105.51  105.75  106.51  107.41  107.85  107.91  108.21  108.27  107.82
      90      90      90      90      90      90      90      90      90      90
      90      90      90      90      90      90      90      90      90      90
      90      90      90      90      90      90      90      90      90   96.58
   96.21   95.74   96.12   96.07   95.55   96.31   96.61   96.61   97.42      95
      95      95      95      95      95      95      95      95      95      95
      95      95      95      95      95      95      95      95      95      95
  3368.3  3388.3  3508.3  3558.3  3598.3  3628.3  3688.3  3738.3  3768.3  3808.3
  3828.3  3848.3  3898.3  3928.3  3948.3  4337.1  4479.9  4529.9  4569.9  4609.9
  4649.9  4719.9  4769.9  4822.9  4870.2  4918.5 4951.49  4951.6 4951.71  4961.8
  4965.8 4966.93    4967 5026.89    5027  5029.4  5042.5 5042.61  5089.1  5138.9
  5148.9  5158.9  5178.9  5206.5  5226.5  5266.5  5478.9  5506.5  5586.5  5598.9
  5646.5  5676.5  5698.9  5738.4  5878.4  5898.9  6038.4  6068.4  6205.1    6268
     110   110.1   109.5   107.8   106.8   106.9   107.9   106.4   106.5   106.9
   106.4   104.8   105.4   105.1   105.7   104.2  102.41  101.64  101.41  101.71
  101.41  100.31  100.41  100.32  100.57  100.38  100.37  105.57  105.57  105.56
  105.56  105.56  105.56  105.51  105.51   105.5  105.49  100.29  100.09    98.7
    98.5    98.8   98.98   98.51   98.66  101.41  102.98  103.81  103.91   103.8
  104.01  105.51  105.75  106.51  107.41  107.85  107.91  108.21  108.27  107.82
      90      90      90      90      90      90      90      90      90      90
      90      90      90      90      90      90      90      90      90      90
      90      90      90      90      90      90      90      90      90   96.58
   96.21   95.74   96.12   96.07   95.55   96.31   96.61   96.61   97.42      95
      95      95      95      95      95      95      95      95      95      95
      95      95      95      95      95      95      95      95      95      95
Pier Skew, UpSta & Num, DnSta & Num=  ,4979.9, 2 ,4979.9, 2 , 0 , 0 , 0 ,,
     1.3     1.3
   92.32    97.1
     1.3     1.3
   94.92    99.7
Pier Skew, UpSta & Num, DnSta & Num=  ,5005.4, 2 ,5005.4, 2 , 0 , 0 , 0 ,,
     1.3     1.3
      88   97.09
     1.3     1.3
    90.6   99.69
BR Coef= 1 , 1 , 1 ,1.05, 0 ,,,.8,0,1.2,0,
WSPro=,,,, 1 ,,,, 0 ,,,, 0 ,,,,-1 ,-1 ,-1 , 0 , 0 , 0 , 0 , 0
BC Design=,, 0 ,, 0 ,,,,,,
BC HTab HWMax=110.63

Type RM Length L Ch R = 1 ,9691.10 ,78,78.7,79
BEGIN DESCRIPTION:
CYPRESSWOOD DRIVE - XS 2
Downstream Section of Bridge/Culvert/Weir
Channel roughness value changed from 0.04 to 0.02 due to the position of the surveyed cross section falling within the limits of the concrete approach  channel.  - JJA 3/28/03
END DESCRIPTION:
XS GIS Cut Line= 6
 3095939.107078613947092.0582673      3095715.06     13946878.19
      3095298.45     13946452.95      3095247.04     13946393.63
       3094734.4     13945887.22 3094550.897654613945732.5372931
#Sta/Elev= 30
    4051     108    4061  108.32    4111  107.97    4131  107.43    4151  107.77
  4360.7  104.66  4550.7  101.45  4700.7   99.52  4770.7   99.31  4910.7    98.1
  4965.8   96.59  4970.5   94.63  4984.2   93.36  4986.4   91.71  5000.5    88.4
  5013.6   91.41  5029.4   96.69  5054.5   98.72  5064.5   98.94  5124.5   98.49
  5364.5   99.44  5474.5  100.63  5484.5  101.21  5494.5  101.02  5504.5  101.46
  5624.5  102.37  5654.5   103.9  5684.5   103.6  5905.1   105.7  5995.1  106.02
#Mann= 4 ,-1 , 0
    4051     .06       0  4360.7     .06       0  4965.8     .02       0
  5029.4     .08       0
#XS Ineff= 2 , 0
       0 4951.17     100 5042.86       0    98.5
Permanent Ineff=
       F       F
Bank Sta=4965.8,5029.4
XS Rating Curve= 0
Exp/Cntr=.5,.3

Type RM Length L Ch R = 1 ,9612.40 ,693,692.8,692
BEGIN DESCRIPTION:
CYPRESSWOOD DRIVE - XS 1
Interpolated XS
END DESCRIPTION:
XS GIS Cut Line= 6
 3096055.506607413947091.5122546      3095760.63     13946809.84
       3095373.7     13946430.77      3095322.28     13946371.45
      3094809.65     13945865.05 3094627.434451713945708.9830116
#Sta/Elev= 30
  4005.8  108.82  4215.8  108.62  4235.8  108.14  4255.8  106.67  4395.8  104.95
  4405.8  104.35  4723.6   99.65  4863.6    98.6  4923.6   97.43  4955.3   98.08
  4965.3   97.65  4985.3    95.1  4995.3   92.74  5000.5   88.29  5005.3   90.65
  5025.3   96.12  5043.8   98.92  5063.8   99.01  5083.8   98.08  5103.8   98.79
  5233.8   99.03  5253.8   98.08  5273.8    97.9  5313.8  100.01  5383.8   99.85
  5553.8  101.42  5563.8  101.91  5754.3  103.33  5794.3  104.66  5994.3  106.45
#Mann= 3 ,-1 , 0
  4005.8     .06       0  4955.3     .04       0  5043.8     .08       0
#XS Ineff= 2 , 0
       0 4951.17   98.39 5042.86       0   98.39
Permanent Ineff=
       F       F
Bank Sta=4955.3,5043.8
XS Rating Curve= 0
Exp/Cntr=.3,.1

Type RM Length L Ch R = 1 ,8919.60 ,1622,1622.2,1623
BEGIN DESCRIPTION:
Cross Section K120-01-00-X08
END DESCRIPTION:
XS GIS Cut Line= 4
 3096475.311173613946669.2610207      3096035.68     13946089.38
      3095803.45     13945953.91 3094966.908506613945622.0247142
#Sta/Elev= 30
  4083.5   107.6  4263.5   105.1  4503.5   103.7  4543.5     103  4563.5   101.6
  4603.5   101.5  4633.5    99.6  4733.5    99.3  4797.5   97.37    4827   97.47
  4848.7   89.87  4892.8   87.52  4919.6   88.08  4948.8   97.42  4973.3   98.16
  4998.3   87.38  5003.8   87.67  5004.8    88.6  5005.6   93.07    5011    97.3
  5070.1   98.33    5210    96.8    5250    98.5    5390   100.4    5520    99.3
    5610    99.9    5660   101.3    5730   100.6    5850   102.9    5980   103.6
#Mann= 6 ,-1 , 0
  4083.5     .05       0  4603.5      .1       0    4827     .05       0
  4973.3     .05       0    5011     .05       0  5070.1     .08       0
#Block Obstruct= 2 ,-1
  4826.4    4951      97    9000    9001      50
Bank Sta=4973.3,5011
XS Rating Curve= 0
Exp/Cntr=.3,.1

Type RM Length L Ch R = 1 ,7297.40 ,35,34.6,34
BEGIN DESCRIPTION:
WEIR U/S IH45 ACCESS - XS 4
XS repeated to eliminate crossing profiles u/s and to model fully expanded flow u/s of weir.
END DESCRIPTION:
XS GIS Cut Line= 6
      3096937.38       13946602.      3097335.26      13945726.5
      3097342.06      13945701.8      3097325.16      13945605.6
      3097169.91      13945201.5      3096943.12      13945020.9
#Sta/Elev= 30
  4019.8  107.82  4069.8  106.62  4219.8  103.82  4239.8  104.02  4329.8  101.62
  4359.8  101.52  4439.8  100.32  4639.8   99.62  4699.8   96.52  4747.4   96.39
  4796.4   94.78  4849.4      94  4894.6    94.6  4946.2    95.8  4966.8   89.49
  4986.8   84.67  5000.5   84.48  5012.2   84.51  5012.8   84.64  5043.5   95.44
  5052.3   96.28    5054   96.44    5057   97.02  5104.7   97.62  5164.7   96.12
  5184.7   95.02  5254.7   95.92  5514.7   97.32  5537.6   96.92  5827.6   99.12
#Mann= 4 ,-1 , 0
  4019.8     .05       0  4329.8     .08       0  4946.2     .05       0
  5052.3     .05       0
Bank Sta=4946.2,5043.5
XS Rating Curve= 0
Exp/Cntr=.7,.5