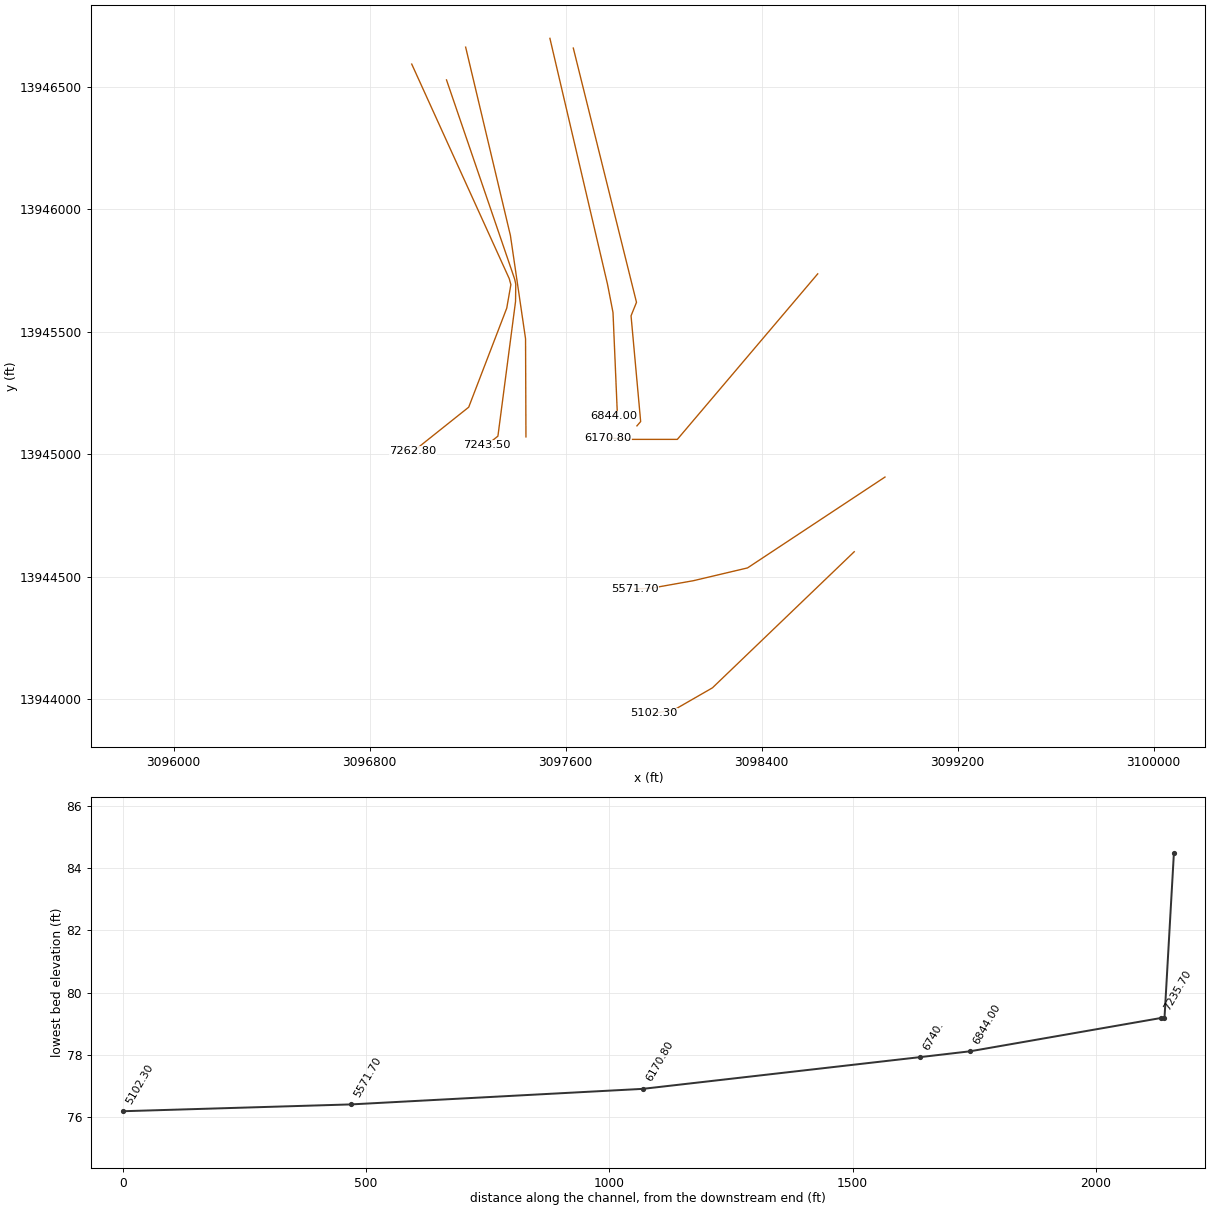
HEC-RAS study K120-01-00.prj: K120-01-00

--- K120-01-00.g03 (geometry) --- (continued)

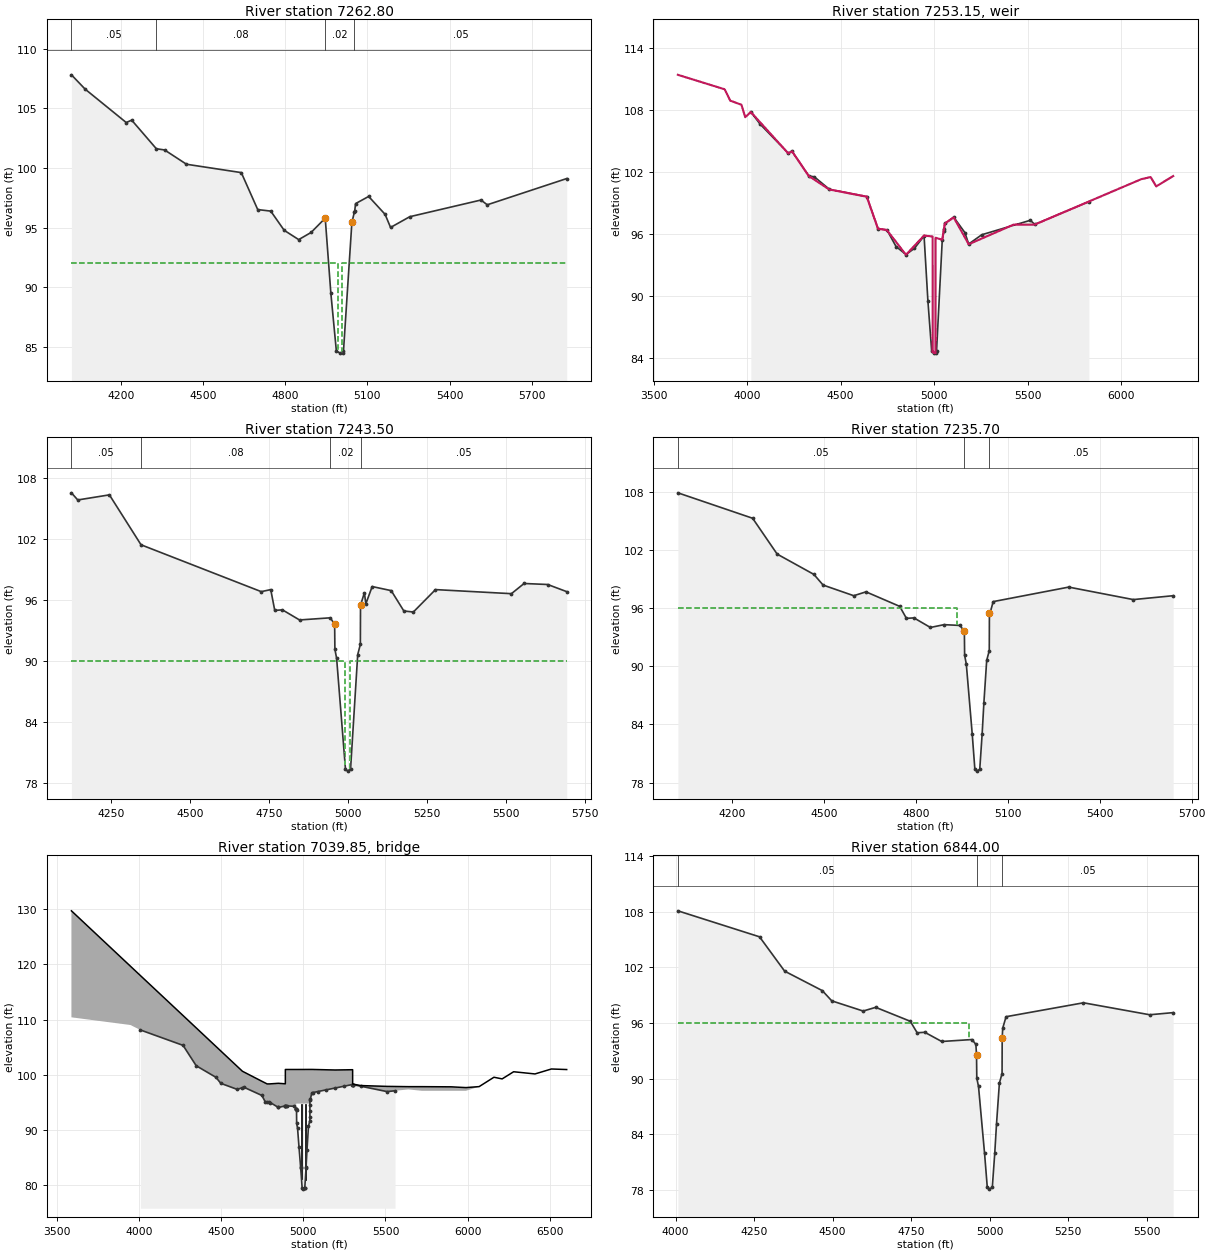
Type RM Length L Ch R = 1 ,7262.80 ,19.3,19.3,19.3
BEGIN DESCRIPTION:
WEIR U/S IH45 ACCESS - XS 3
Upstream Section of Bridge/Culvert/Weir
Cont/exp coefficients raised to model weir directly u/s of bridge, most flow in the channel.
END DESCRIPTION:
XS GIS Cut Line= 6
      3096972.11      13946591.6      3097369.99     13945716.12
      3097376.79     13945691.45      3097359.89     13945595.26
      3097204.64     13945191.15      3096977.84      13945010.4
#Sta/Elev= 30
  4019.8  107.82  4069.8  106.62  4219.8  103.82  4239.8  104.02  4329.8  101.62
  4359.8  101.52  4439.8  100.32  4639.8   99.62  4699.8   96.52  4747.4   96.39
  4796.4   94.78  4849.4      94  4894.6    94.6  4946.2    95.8  4966.8   89.49
  4986.8   84.67  5000.5   84.48  5012.2   84.51  5012.8   84.64  5043.5   95.44
  5052.3   96.28    5054   96.44    5057   97.02  5104.7   97.62  5164.7   96.12
  5184.7   95.02  5254.7   95.92  5514.7   97.32  5537.6   96.92  5827.6   99.12
#Mann= 4 ,-1 , 0
  4019.8     .05       0  4329.8     .08       0  4946.2     .02       0
  5052.3     .05       0
#XS Ineff= 2 , 0
       0  4991.8      92  5007.8       0      92
Permanent Ineff=
       F       F
Bank Sta=4946.2,5043.5
XS Rating Curve= 0
Exp/Cntr=.7,.5

Type RM Length L Ch R = 5 ,7253.15 ,,,
BEGIN DESCRIPTION:
Structure ID: K120-01-00-S2a
END DESCRIPTION:
IW Pilot Flow=0
#Inline Weir SE= 30
  3629.8   111.4  3879.8     110  3909.8   108.9  3969.8   108.5  3989.8   107.3
  4019.8   107.8  4219.8   103.8  4239.8     104  4329.8   101.6  4439.8   100.3
  4639.8    99.6  4699.8    96.5  4747.4   96.37  4849.4   93.98    4946   95.84
  4991.8   95.75  4992.3   84.54  5000.5   84.46  5007.7   84.48  5007.8   95.63
  5043.5   95.43    5057      97  5104.7    97.6  5184.7      95  5424.7    96.9
  5537.6    96.9  6107.6   101.3  6157.6   101.5  6187.6   100.6    6278   101.6
IW Dist,WD,Coef,Skew,MaxSub,Min_El,Is_Ogee,SpillHt,DesHd
10,1,3,0,.95,, 0 ,,,0,0,

Type RM Length L Ch R = 1 ,7243.50 ,7.8,7.8,7.8
BEGIN DESCRIPTION:
WEIR U/S IH45 ACCESS - XS 1 & IH45 - XS 4
Cross Section FIELD_DS WEIR U/S IH45 ACCESS
Located At: WEIR U/S IH45 ACCESS
Cont/exp coefficients raised to model weir directly u/s of bridge, most flow in the channel.
END DESCRIPTION:
XS GIS Cut Line= 6
      3097114.07      13946526.9      3097392.07     13945714.42
      3097396.75     13945693.15      3097395.86     13945622.89
      3097323.89     13945072.94      3097276.74      13945035.7
#Sta/Elev= 30
  4126.1   106.5  4146.1   105.8  4246.1   106.3  4346.1   101.4  4726.1    96.8
  4756.1      97  4768.8   94.96  4793.2   95.01  4847.1   94.02  4944.1   94.23
  4958.1   93.61  4958.9   91.15  4964.4   90.24  4992.2   79.43  4998.8   79.18
  5008.4   79.37    5031   90.61  5039.4   91.63  5039.9   95.47  5052.2   96.69
  5056.7    95.6  5076.7    97.3  5136.9    96.9  5176.9    94.9  5206.9    94.8
  5276.9      97  5516.9    96.6  5556.9    97.6  5631.6    97.5  5691.6    96.8
#Mann= 4 ,-1 , 0
  4126.1     .05       0  4346.1     .08       0  4944.1     .02       0
  5039.9     .05       0
#XS Ineff= 2 , 0
       0  4991.8      90  5007.8       0      90
Permanent Ineff=
       F       F
Bank Sta=4958.1,5039.9
XS Rating Curve= 0
Exp/Cntr=.7,.5

Type RM Length L Ch R = 1 ,7235.70 ,391.7,391.7,391.7
BEGIN DESCRIPTION:
WEIR U/S IH45 ACCESS - XS 2 & IH45 - XS 3
Upstream Section of Bridge/Culvert/Weir
END DESCRIPTION:
XS GIS Cut Line= 4
      3097192.19      13946660.6       3097374.9     13945891.86
      3097436.68     13945470.32      3097438.33       13945070.
#Sta/Elev= 30
  4023.1 107.928  4267.1   105.3  4347.1   101.6  4467.1    99.5  4497.1    98.4
  4597.1    97.3  4637.1    97.7  4747.1    96.2  4769.1   94.96  4793.5   95.01
  4847.3   94.02  4891.9   94.31  4943.9   94.23  4958.2   93.61    4959   91.15
  4964.5   90.24  4983.8   83.02  4992.3   79.43  4998.9   79.18  5008.4   79.37
  5016.2   83.03  5021.9   86.24    5031   90.61  5039.5   91.63  5039.9   95.47
  5041.6   95.45  5052.2   96.69  5298.8   98.19  5509.6    96.9  5639.6    97.3
#Mann= 3 ,-1 , 0
  4023.1     .05       0  4958.2     .02       0  5039.9     .05       0
#XS Ineff= 2 , 0
       0  4933.9      96  5049.9       0      96
Permanent Ineff=
       F       F
Bank Sta=4958.2,5039.9
XS Rating Curve= 0
Exp/Cntr=.5,.3

Type RM Length L Ch R = 3 ,7039.85 ,,,
BEGIN DESCRIPTION:
IH45
Structure ID: K120-01-00-S2
END DESCRIPTION:
Bridge Culvert--1,0,-1,-1, 0
Deck Dist Width WeirC Skew NumUp NumDn MinLoCord MaxHiCord MaxSubmerge Is_Ogee
10,374,2.6,0, 43, 43, , , .95, 0, 0,0,,
  3587.1  3947.1  4007.1  4267.1  4347.1  4467.1  4497.1  4597.1  4628.7  4637.1
  4747.1  4769.1  4778.7  4793.5  4847.3 4890.09  4890.2  4943.9 4956.08 4956.15
 5039.69  5039.8  5039.9  5041.6  5052.2  5193.9    5300 5300.11  5348.2  5509.6
  5639.6  5720.7  5900.7  5950.7  5970.7  5990.7  6070.7  6160.7  6210.7  6280.7
  6410.7  6510.7  6603.9
  129.75  119.67  117.99  110.72  108.48  105.12  104.28  101.48   100.6  100.47
   98.78   98.45    98.3    98.3   98.41   98.32  100.92  100.92  100.92  100.92
  100.93  100.93  100.93  100.93  100.93  100.83  100.88   98.28      98   97.85
    97.8    97.8   97.77   97.69   97.66   97.63   97.81   99.51   99.21  100.51
  100.11  101.01  100.91
   110.4     109   108.1   105.3   101.6    99.5    98.4    97.3   97.62    97.7
    96.2   94.96   94.98   95.01   94.02    94.3    94.3   94.23    93.7   94.72
   94.73   94.51   95.47   95.45   96.69   97.55   98.18   98.18   97.89    96.9
    97.3    96.8      97    96.3    96.6    96.5    97.8    99.5    99.2   100.5
   100.1     101   100.9
  3587.1  3947.1  4007.1  4267.1  4347.1  4467.1  4497.1  4597.1  4628.7  4637.1
  4747.1  4769.1  4778.7  4793.5  4847.3 4890.09  4890.2  4943.9 4956.08 4956.15
 5039.69  5039.8  5039.9  5041.6  5052.2  5193.9    5300 5300.11  5348.2  5509.6
  5639.6  5720.7  5900.7  5950.7  5970.7  5990.7  6070.7  6160.7  6210.7  6280.7
  6410.7  6510.7  6603.9
  129.75  119.67  117.99  110.72  108.48  105.12  104.28  101.48   100.6  100.47
   98.78   98.45    98.3    98.3   98.41   98.32  100.92  100.92  100.92  100.92
  100.93  100.93  100.93  100.93  100.93  100.83  100.88   98.28      98   97.85
    97.8    97.8   97.77   97.69   97.66   97.63   97.81   99.51   99.21  100.51
  100.11  101.01  100.91
   110.4     109   108.1   105.3   101.6    99.5    98.4    97.3   97.62    97.7
    96.2   94.96   94.98   95.01   94.02    94.3    94.3   94.23    93.7   94.72
   94.73   94.42   94.42   95.45   96.69   97.55   98.18   98.18   97.89    96.9
    97.3    96.8      97    96.3    96.6    96.5    97.8    99.5    99.2   100.5
   100.1     101   100.9
Pier Skew, UpSta & Num, DnSta & Num=  ,4988.6, 2 ,4988.6, 2 , 0 , 0 , 0 ,,
       3       3
   79.36      96
       3       3
   78.31      96
Pier Skew, UpSta & Num, DnSta & Num=  ,5011.6, 2 ,5011.6, 2 , 0 , 0 , 0 ,,
       3       3
   79.17      96
       3       3
   78.12      96
BR Coef= 1 , 1 , 1 ,1.05, 0 ,,,.8,-1,1.2,0,
WSPro=,,,, 1 ,,,, 0 ,,,, 0 ,,,,-1 ,-1 ,-1 , 0 , 0 , 0 , 0 , 0
BR U #Sta/Elev= 58
  4007.1   108.1  4267.1   105.3  4347.1   101.6  4467.1    99.5  4497.1    98.4
  4597.1    97.3  4628.7   97.62  4637.1    97.7  4747.1    96.2  4769.1   94.96
  4778.7   94.98  4793.5   95.01  4798.7   94.91  4845.8   94.05  4847.3   94.02
 4890.09    94.3  4890.2    94.3 4890.31    94.3  4891.9   94.31  4900.6    94.3
  4943.9   94.23  4954.9   93.75 4955.96   93.71 4956.08    93.7 4956.15    93.7
  4958.2   93.61    4959   91.15  4964.5   90.24  4973.3   86.84    4983   83.24
  4983.8   83.02  4992.3   79.43  4998.9   79.18  5008.3   79.37  5008.4   79.37
  5016.2   83.03  5016.4   83.24  5021.9   86.24    5031   90.61  5039.5   91.63
 5039.57    92.3 5039.69   93.45  5039.8   94.51  5039.9   95.47  5041.6   95.45
  5052.2   96.69  5055.8   96.71  5086.7    96.9  5140.6   97.23  5193.9   97.55
    5246   97.87  5298.8   98.19 5299.89   98.18    5300   98.18 5300.11   98.18
  5348.2   97.89  5509.6    96.9  5558.2   97.05
BR U #Mann= 3
  4007.1     .05  4958.2     .02  5039.9     .05
BR U Banks=4958.2,5039.9
BR D #Sta/Elev= 58
  4007.1   108.1  4267.1   105.3  4347.1   101.6  4467.1    99.5  4497.1    98.4
  4597.1    97.3  4628.7   97.62  4637.1    97.7  4747.1    96.2  4769.1   94.96
  4778.7   94.98  4793.5   95.01  4798.7   94.91  4845.8   94.05  4847.3   94.02
 4890.09    94.3  4890.2    94.3 4890.31    94.3  4891.9   94.31  4900.6    94.3
  4943.9   94.23  4954.9   93.75 4955.96   93.71 4956.08    93.7 4956.15    93.7
  4958.2   92.56    4959    90.1  4964.5   89.19  4973.3   85.79    4983   82.19
  4983.8   81.97  4992.3   78.38  4998.9   78.13  5008.3   78.32  5008.4   78.32
  5016.2   81.98  5016.4   82.19  5021.9   85.19    5031   89.56  5039.5   90.58
 5039.57   91.25 5039.69    92.4  5039.8   93.46  5039.9   94.42  5041.6   95.45
  5052.2   96.69  5055.8   96.71  5086.7    96.9  5140.6   97.23  5193.9   97.55
    5246   97.87  5298.8   98.19 5299.89   98.18    5300   98.18 5300.11   98.18
  5348.2   97.89  5509.6    96.9  5558.2   97.05
BR D #Mann= 3
  4007.1     .05  4958.2     .02  5039.9     .05
BR D Banks=4958.2,5039.9
BC Design=,, 0 ,, 0 ,,,,,,
BC HTab HWMax=132.5

Type RM Length L Ch R = 1 ,6844.00 ,132,104,85
BEGIN DESCRIPTION:
IH45 - XS 2
Downstream Section of Bridge/Culvert/Weir
END DESCRIPTION:
XS GIS Cut Line= 5
      3097536.08      13946696.6      3097771.39     13945692.02
      3097793.61     13945577.47      3097810.98     13945172.33
       3097795.8      13945154.7
#Sta/Elev= 30
  4007.1   108.1  4267.1   105.3  4347.1   101.6  4467.1    99.5  4497.1    98.4
  4597.1    97.3  4637.1    97.7  4747.1    96.2  4769.1   94.96  4793.5   95.01
  4847.3   94.02  4943.9   94.23 4956.15    93.7  4958.2   92.54    4959   90.08
  4964.5   89.17  4983.8   81.95  4992.3   78.36  4998.9   78.11  5008.4    78.3
  5016.2   81.96  5021.9   85.17    5031   89.54  5039.5   90.56  5039.9    94.4
  5041.6   95.45  5052.2   96.69  5298.8   98.19  5509.6    96.9 5584.33   97.13
#Mann= 3 ,-1 , 0
  4007.1     .05       0  4958.2     .02       0  5039.9     .05       0
#XS Ineff= 2 , 0
       0  4933.9      96  5049.9       0      96
Permanent Ineff=
       F       F
Bank Sta=4958.2,5039.9
XS Rating Curve= 0
Exp/Cntr=.5,.3

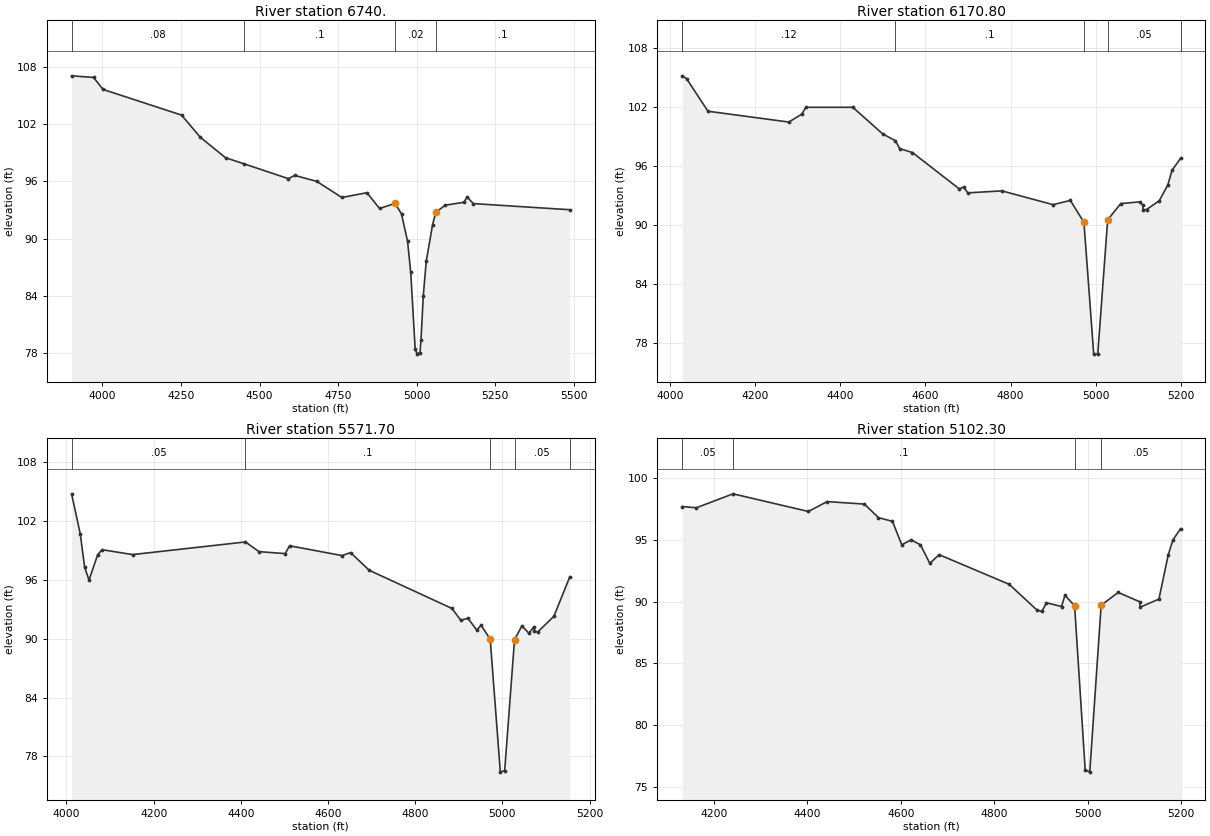
Type RM Length L Ch R = 1 ,6740.   ,616,569.2,525
BEGIN DESCRIPTION:
IH45 - XS 1
END DESCRIPTION:
XS GIS Cut Line= 5
      3097631.56      13946656.9      3097889.46     13945619.11
      3097867.26     13945564.09      3097906.45     13945132.55
      3097891.28     13945114.98
#Sta/Elev= 30
  3901.7  107.04  3971.7  106.87  4001.7  105.62  4251.7  102.93  4311.7   100.6
  4391.7   98.47  4451.7   97.82  4591.7   96.28  4611.7   96.62  4681.7      96
  4761.7   94.31  4841.7   94.81  4881.7   93.16  4931.7   93.69  4951.7   92.58
    4971   89.71    4981   86.49 4995.17   78.47 5001.33   77.92 5010.53   78.09
 5013.72   79.44    5021   84.03  5030.4   87.65  5050.4   91.43  5060.4   92.74
  5090.4    93.5  5150.4   93.81  5160.4   94.35  5180.4   93.67  5486.9   93.03
#Mann= 4 ,-1 , 0
  3901.7     .08       0  4451.7      .1       0  4931.7     .02       0
  5060.4      .1       0
Bank Sta=4931.7,5060.4
XS Rating Curve= 0
Exp/Cntr=.3,.1

Type RM Length L Ch R = 1 ,6170.80 ,599,599.1,599.1
BEGIN DESCRIPTION:
Cross Section K120-01-00-X7
END DESCRIPTION:
XS GIS Cut Line= 4
      3098629.14      13945735.4      3098056.15      13945059.8
      3097862.62      13945059.8      3097773.01     13945065.64
#Sta/Elev= 30
  4029.7   105.2  4039.7   104.9  4089.7   101.6  4279.7   100.5  4309.7   101.3
  4319.7     102  4429.7     102  4499.7    99.3  4529.7    98.6  4539.7    97.8
  4569.7    97.4  4679.7    93.7  4689.7    93.9  4699.7    93.3  4779.7    93.5
  4899.7    92.1  4940.3   92.53  4972.2    90.3  4995.2    76.9  5004.7   76.93
  5027.9   90.55  5058.6   92.21  5102.7   92.38  5110.8   92.06  5111.2   91.58
  5119.1    91.6  5149.1    92.5  5169.1    94.1  5179.1    95.6  5198.9    96.8
#Mann= 5 ,-1 , 0
  4029.7     .12       0  4529.7      .1       0  4972.2     .02       0
  5027.9     .05       0  5198.9      .2       0
Bank Sta=4972.2,5027.9
XS Rating Curve= 0
Exp/Cntr=.3,.1

Type RM Length L Ch R = 1 ,5571.70 ,469.4,469.4,469
BEGIN DESCRIPTION:
Cross Section K120-01-00-X6
END DESCRIPTION:
XS GIS Cut Line= 5
 3098903.656131913944906.0141946      3098342.57     13944535.16
      3098121.95     13944483.07      3097947.78     13944452.11
      3097881.52     13944449.32
#Sta/Elev= 30
  4011.8   104.8  4031.8   100.7  4041.8    97.3  4051.8      96  4071.8    98.6
  4081.8    99.1  4151.8    98.6  4410.6   99.89  4441.8    98.9  4501.8    98.7
  4511.8    99.5  4631.8    98.5  4651.8    98.8  4694.4      97  4884.4    93.1
  4904.4    91.9    4921    92.1    4941    90.9    4951   91.38    4972   89.98
  4995.2    76.4  5005.2   76.56  5027.8   89.93  5044.7   91.32  5060.7   90.58
  5072.4   91.24  5072.7   90.78    5081    90.7    5118    92.3  5154.3    96.3
#Mann= 5 ,-1 , 0
  4011.8     .05       0  4410.6      .1       0    4972     .02       0
  5027.8     .05       0  5154.3      .2       0
Bank Sta=4972,5027.8
XS Rating Curve= 0
Exp/Cntr=.3,.1

Type RM Length L Ch R = 1 ,5102.30 ,214.9,224.3,226.9
BEGIN DESCRIPTION:
Cross Section K120-01-00-X5
END DESCRIPTION:
XS GIS Cut Line= 4
 3098778.195328613944601.2399656      3098199.37     13944045.69
      3098044.54     13943956.67      3097959.64     13943941.51
#Sta/Elev= 30
    4132    97.7    4162    97.6  4240.5   98.73    4402    97.3    4442    98.1
    4522    97.9    4552    96.8    4582    96.5    4602    94.6    4622      95
    4642    94.6    4662    93.1    4682    93.8    4832    91.4    4892    89.3
    4902    89.2    4912    89.9  4944.3    89.6  4951.5   90.51  4972.2   89.66
  4994.9   76.37  5004.7   76.18  5029.1    89.7  5065.6   90.74    5112   89.98
  5112.3   89.54  5152.9    90.2  5172.9    93.8  5182.9      95  5199.1    95.9
#Mann= 4 ,-1 , 0
    4132     .05       0  4240.5      .1       0  4972.2     .02       0
  5029.1     .05       0
Bank Sta=4972.2,5029.1
XS Rating Curve= 0
Exp/Cntr=.3,.1