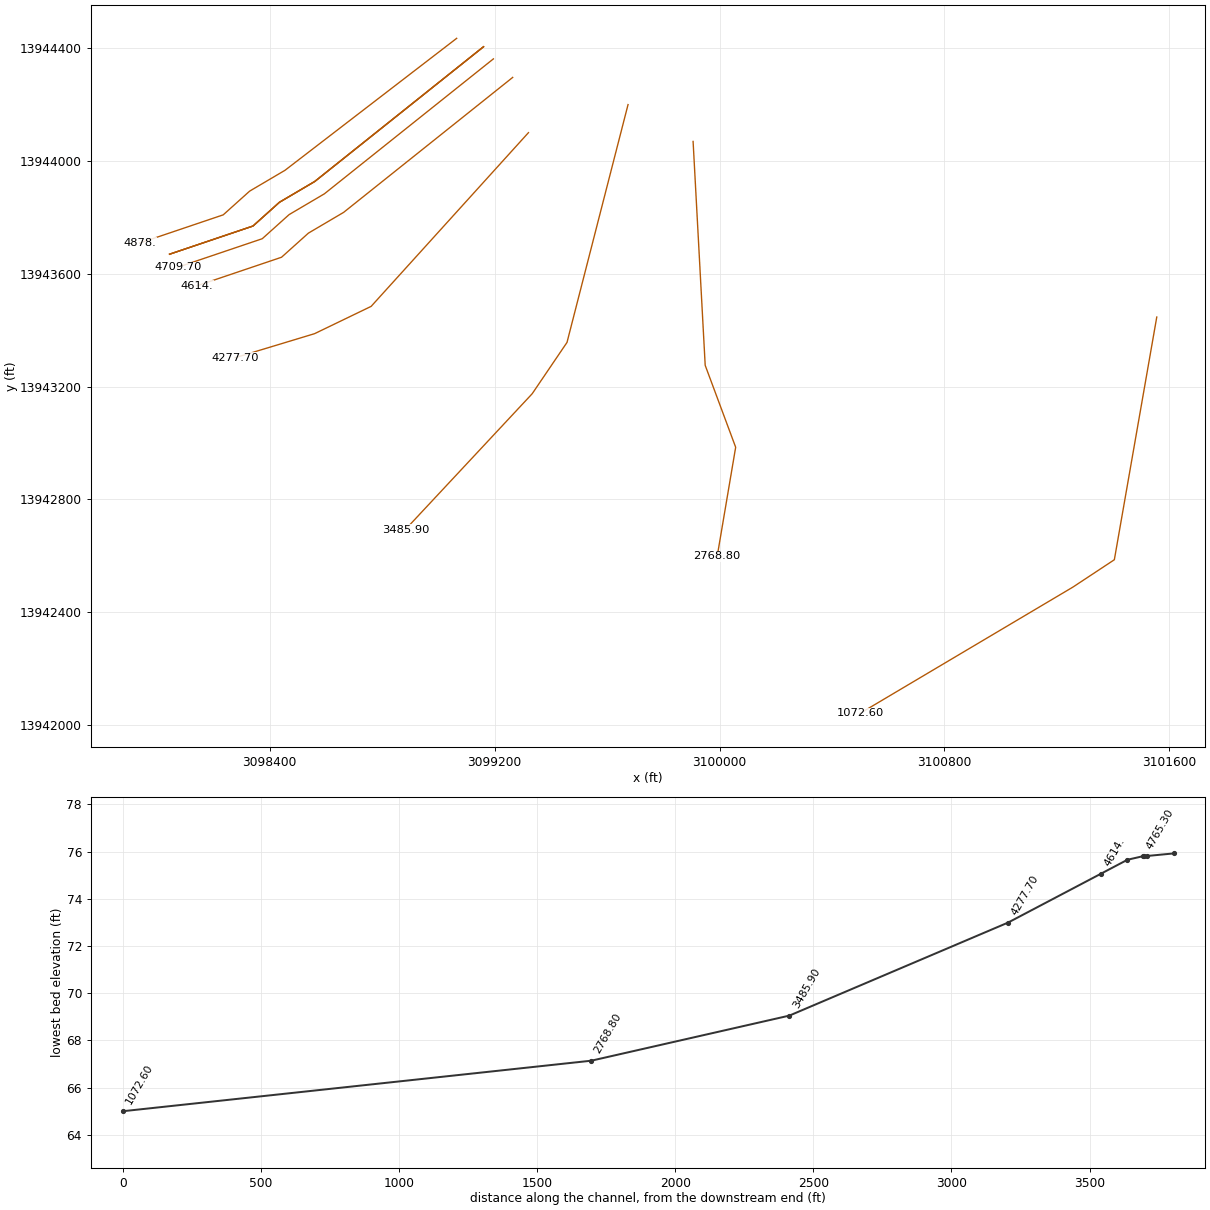
HEC-RAS study K120-01-00.prj: K120-01-00

--- K120-01-00.g03 (geometry) --- (continued)

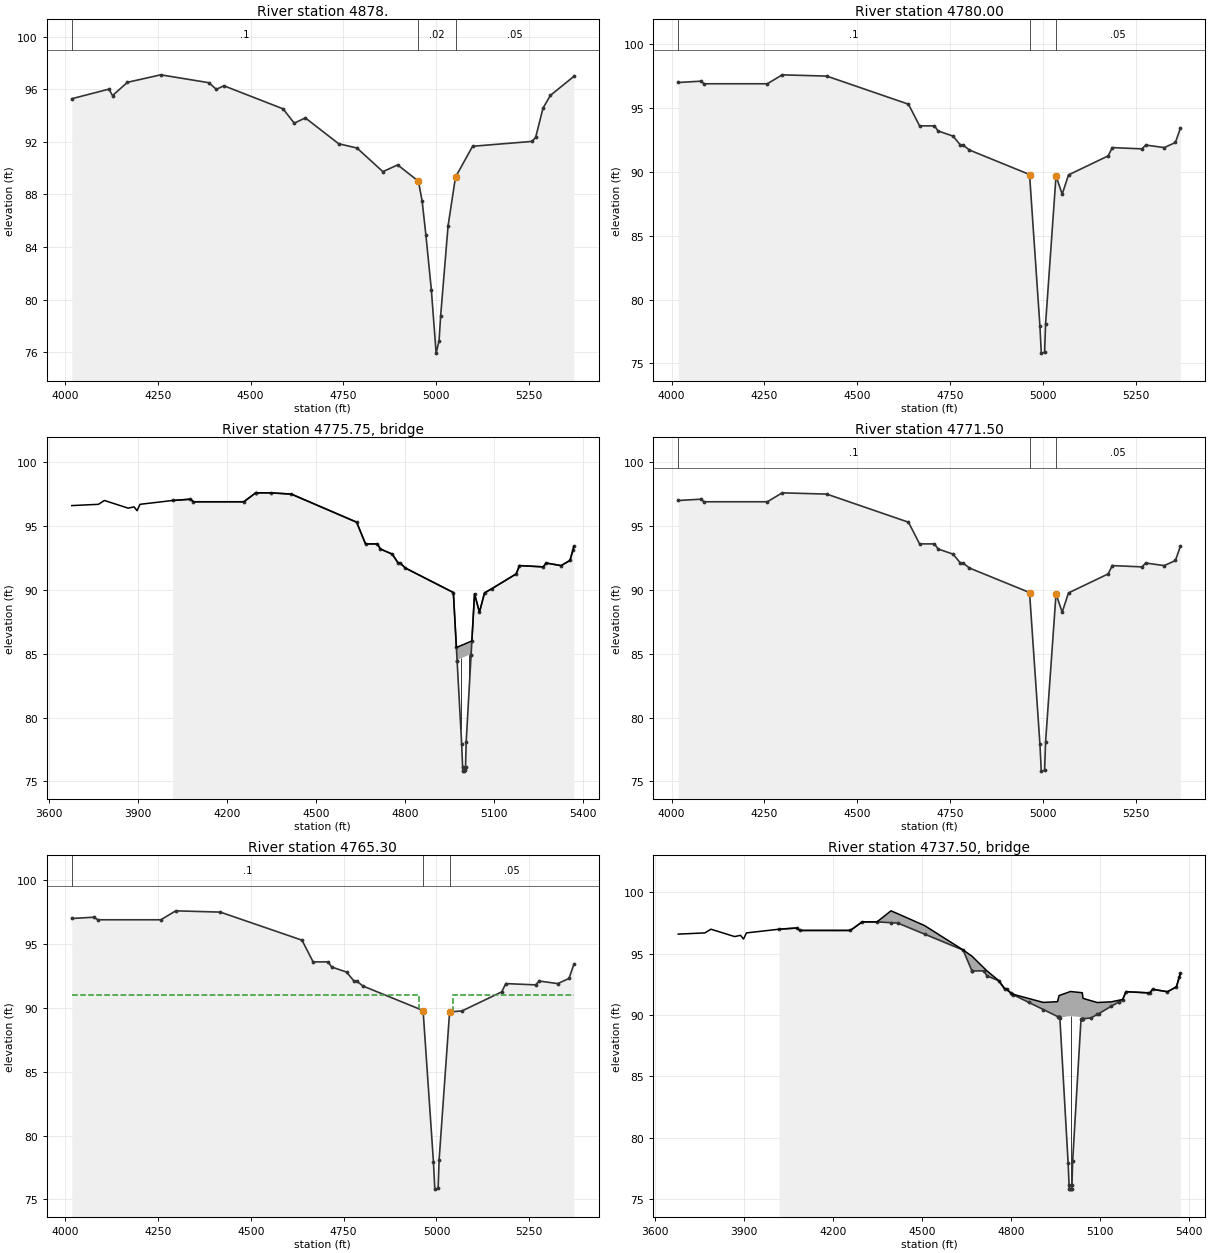
Type RM Length L Ch R = 1 ,4878.   ,101,98,92
BEGIN DESCRIPTION:
Pipeline - XS 4
END DESCRIPTION:
XS GIS Cut Line= 5
      3099064.86     13944434.47      3098454.26     13943966.79
      3098328.48     13943892.94      3098234.51     13943808.87
      3097937.76     13943708.96
#Sta/Elev= 30
  4017.6   95.29  4117.6   96.02  4127.6   95.53  4167.6   96.54  4257.6   97.11
  4387.6   96.51  4407.6      96  4427.6   96.28  4587.6   94.52  4617.6   93.43
  4647.6   93.83  4737.6   91.86  4786.7   91.54  4856.7   89.74  4896.7   90.25
  4952.6   89.01  4962.6    87.5  4972.6   84.95 4987.42   80.76 5000.37   75.92
 5008.22   76.86  5012.6   78.78  5032.6   85.62  5052.6   89.32  5098.7   91.67
  5258.7   92.04  5268.7   92.34  5288.7   94.58  5308.7   95.55  5371.8   96.99
#Mann= 3 ,-1 , 0
  4017.6      .1       0  4952.6     .02       0  5052.6     .05       0
Bank Sta=4952.6,5052.6
XS Rating Curve= 0
Exp/Cntr=.5,.3

Type RM Length L Ch R = 1 ,4780.00 ,8.5,8.5,8.5
BEGIN DESCRIPTION:
Pipeline - XS 3
Upstream Section of Bridge/Culvert/Weir
END DESCRIPTION:
XS GIS Cut Line= 5
 3099160.338906413944404.6378834       3098560.1     13943927.16
      3098434.32     13943853.31      3098340.35     13943769.24
       3098043.6     13943669.33
#Sta/Elev= 29
  4017.9   97.01  4077.9   97.11  4087.9   96.91  4257.9   96.91  4297.9   97.61
  4417.9   97.51  4637.9   95.31  4667.9   93.61  4707.9   93.61  4717.9   93.21
  4757.9   92.81  4777.9   92.11  4784.9   92.11  4802.1   91.72    4964    89.8
    4992   77.91  4995.6   75.81  5004.5   75.86  5007.2   78.12  5035.3   89.69
  5051.9   88.26  5068.9   89.77  5175.7   91.26  5186.8   91.91  5266.8   91.81
  5276.8   92.11  5326.8   91.91  5356.8   92.31    5370   93.41
#Mann= 3 ,-1 , 0
  4017.9      .1       0    4964     .02       0  5035.3     .05       0
#XS Ineff= 2 , 0
       0    4954   89.79  5045.3       0   88.25
Permanent Ineff=
       F       F
Bank Sta=4964,5035.3
XS Rating Curve= 0
Exp/Cntr=.5,.3

Type RM Length L Ch R = 3 ,4775.75 ,,,
BEGIN DESCRIPTION:
PL1_K120-01-00-S1
END DESCRIPTION:
Bridge Culvert--1,0,-1,-1, 0
Deck Dist Width WeirC Skew NumUp NumDn MinLoCord MaxHiCord MaxSubmerge Is_Ogee
5,1,2.6,0, 49, 49, , , .95, 0, 0,0,,
  3677.9  3767.9  3787.9  3867.9  3887.9  3897.9  3907.9  4017.9  4077.9  4087.9
  4257.9  4297.9  4299.3  4347.9  4417.9  4637.9  4667.9  4707.9  4717.9  4757.9
  4777.9  4784.9  4802.1    4964  4974.1 4976.61  4976.7    4992  4995.1  4995.6
  4999.6  5004.5  5004.9  5007.2 5023.59  5023.7  5026.3  5035.3  5051.9  5068.9
  5094.4  5175.7  5186.8  5266.8  5276.8  5326.8  5356.8  5366.8    5370
    96.6    96.7      97    96.4    96.5    96.2    96.7      97    97.1    96.9
    96.9    97.6    97.6    97.6    97.5    95.3    93.6    93.6    93.2    92.8
    92.1    92.1   91.71   89.79   85.51   85.51   85.51   85.66   85.69   85.69
   85.73   85.78   85.79   85.81   85.97   85.97      86   89.68   88.25   89.76
    90.1   91.25    91.9    91.8    92.1    91.9    92.3    93.1    93.4
    96.6    96.7      97    96.4    96.5    96.2    96.7      97    97.1    96.9
    96.9    97.6    97.6    97.6    97.5    95.3    93.6    93.6    93.2    92.8
    92.1    92.1   91.71   89.79    85.5   84.44   84.51   84.66   84.69   84.69
   84.73   84.78   84.79   84.81   84.97    84.9   85.97   89.68   88.25   89.76
    90.1   91.25    91.9    91.8    92.1    91.9    92.3    93.1    93.4
  3677.9  3767.9  3787.9  3867.9  3887.9  3897.9  3907.9  4017.9  4077.9  4087.9
  4257.9  4297.9  4299.3  4347.9  4417.9  4637.9  4667.9  4707.9  4717.9  4757.9
  4777.9  4784.9  4802.1    4964  4974.1 4976.61  4976.7    4992  4995.1  4995.6
  4999.6  5004.5  5004.9  5007.2 5023.59  5023.7  5026.3  5035.3  5051.9  5068.9
  5094.4  5175.7  5186.8  5266.8  5276.8  5326.8  5356.8  5366.8    5370
    96.6    96.7      97    96.4    96.5    96.2    96.7      97    97.1    96.9
    96.9    97.6    97.6    97.6    97.5    95.3    93.6    93.6    93.2    92.8
    92.1    92.1   91.71   89.79   85.51   85.51   85.51   85.66   85.69   85.69
   85.73   85.78   85.79   85.81   85.97   85.97      86   89.68   88.25   89.76
    90.1   91.25    91.9    91.8    92.1    91.9    92.3    93.1    93.4
    96.6    96.7      97    96.4    96.5    96.2    96.7      97    97.1    96.9
    96.9    97.6    97.6    97.6    97.5    95.3    93.6    93.6    93.2    92.8
    92.1    92.1   91.71   89.79    85.5   84.44   84.51   84.66   84.69   84.69
   84.73   84.78   84.79   84.81   84.97    84.9   85.97   89.68   88.25   89.76
    90.1   91.25    91.9    91.8    92.1    91.9    92.3    93.1    93.4
Pier Skew, UpSta & Num, DnSta & Num=  ,4989.1, 2 ,4989.1, 2 , 0 , 0 , 0 ,,
     1.3     1.3
   77.86   85.64
     1.3     1.3
   77.86   85.64
Pier Skew, UpSta & Num, DnSta & Num=  ,5017.3, 2 ,5017.3, 2 , 0 , 0 , 0 ,,
     1.3     1.3
      81   85.91
     1.3     1.3
      81   85.91
BR Coef= 1 , 1 , 1 ,.9, 0 ,,,.8,-1,1.2,0,
WSPro=,,,, 1 ,,,, 0 ,,,, 0 ,,,,-1 ,-1 ,-1 , 0 , 0 , 0 , 0 , 0
BR U #Sta/Elev= 42
  4017.9      97  4077.9    97.1  4087.9    96.9  4257.9    96.9  4297.9    97.6
  4299.3    97.6  4347.9    97.6  4417.9    97.5  4637.9    95.3  4667.9    93.6
  4707.9    93.6  4717.9    93.2  4757.9    92.8  4777.9    92.1  4784.9    92.1
  4802.1   91.71    4964   89.79  4974.1    85.5 4976.61   84.44  4976.7    84.4
    4992    77.9  4995.1   76.13  4995.6    75.8  4999.6   75.83  5004.5   75.85
  5004.9   76.14  5007.2   78.11 5023.59   84.86  5023.7    84.9  5026.3   85.97
  5035.3   89.68  5051.9   88.25  5068.9   89.76  5094.4    90.1  5175.7   91.25
  5186.8    91.9  5266.8    91.8  5276.8    92.1  5326.8    91.9  5356.8    92.3
  5366.8    93.1    5370    93.4
BR U #Mann= 3
  4017.9      .1    4964     .02  5035.3     .05
BR U Banks=4964,5035.3
BR D #Sta/Elev= 42
  4017.9      97  4077.9    97.1  4087.9    96.9  4257.9    96.9  4297.9    97.6
  4299.3    97.6  4347.9    97.6  4417.9    97.5  4637.9    95.3  4667.9    93.6
  4707.9    93.6  4717.9    93.2  4757.9    92.8  4777.9    92.1  4784.9    92.1
  4802.1   91.71    4964   89.79  4974.1    85.5 4976.61   84.44  4976.7    84.4
    4992    77.9  4995.1   76.13  4995.6    75.8  4999.6   75.83  5004.5   75.85
  5004.9   76.14  5007.2   78.11 5023.59   84.86  5023.7    84.9  5026.3   85.97
  5035.3   89.68  5051.9   88.25  5068.9   89.76  5094.4    90.1  5175.7   91.25
  5186.8    91.9  5266.8    91.8  5276.8    92.1  5326.8    91.9  5356.8    92.3
  5366.8    93.1    5370    93.4
BR D #Mann= 3
  4017.9      .1    4964     .02  5035.3     .05
BR D Banks=4964,5035.3
BC Design=,, 0 ,, 0 ,,,,,,
BC HTab HWMax=97.61

Type RM Length L Ch R = 1 ,4771.50 ,6.2,6.2,6.2
BEGIN DESCRIPTION:
Pipeline - XS 2  &  EAST NORTH HILL - XS 4
Downstream Section of Bridge/Culvert/Weir
END DESCRIPTION:
XS GIS Cut Line= 5
 3099160.338906413944404.6378834       3098560.1     13943927.16
      3098434.32     13943853.31      3098340.35     13943769.24
       3098043.6     13943669.33
#Sta/Elev= 29
  4017.9      97  4077.9    97.1  4087.9    96.9  4257.9    96.9  4297.9    97.6
  4417.9    97.5  4637.9    95.3  4667.9    93.6  4707.9    93.6  4717.9    93.2
  4757.9    92.8  4777.9    92.1  4784.9    92.1  4802.1   91.71    4964   89.79
    4992    77.9  4995.6    75.8  5004.5   75.85  5007.2   78.11  5035.3   89.68
  5051.9   88.25  5068.9   89.76  5175.7   91.25  5186.8    91.9  5266.8    91.8
  5276.8    92.1  5326.8    91.9  5356.8    92.3    5370    93.4
#Mann= 3 ,-1 , 0
  4017.9      .1       0    4964     .02       0  5035.3     .05       0
#XS Ineff= 2 , 0
       0 4957.33   89.79 5041.97       0   88.25
Permanent Ineff=
       F       F
Bank Sta=4964,5035.3
XS Rating Curve= 0
Exp/Cntr=.5,.3

Type RM Length L Ch R = 1 ,4765.30 ,55.6,55.6,55.6
BEGIN DESCRIPTION:
Pipeline - XS 1  &  EAST NORTH HILL - XS 3
Upstream Section of Bridge/Culvert/Weir
END DESCRIPTION:
XS GIS Cut Line= 5
 3099160.338906413944404.6378834       3098560.1     13943927.16
      3098434.32     13943853.31      3098340.35     13943769.24
       3098043.6     13943669.33
#Sta/Elev= 28
  4017.9      97  4077.9    97.1  4087.9    96.9  4257.9    96.9  4297.9    97.6
  4417.9    97.5  4637.9    95.3  4667.8    93.6  4707.9    93.6  4717.9    93.2
  4757.9    92.8  4777.9    92.1  4784.9    92.1  4802.1   91.71    4964   89.79
    4992    77.9  4995.6    75.8  5004.5   75.85  5007.2   78.11  5035.4   89.68
  5068.9   89.76  5175.7   91.25  5186.8    91.9  5266.8    91.8  5276.8    92.1
  5326.8    91.9  5356.8    92.3    5370    93.4
#Mann= 3 ,-1 , 0
  4017.9      .1       0    4964     .02       0  5035.4     .05       0
#XS Ineff= 2 , 0
       0    4954   91.03  5045.4       0   91.02
Permanent Ineff=
       F       F
Bank Sta=4964,5035.4
XS Rating Curve= 0
Exp/Cntr=.5,.3

Type RM Length L Ch R = 3 ,4737.50 ,,,
BEGIN DESCRIPTION:
EAST NORTH HILL
Structure ID: K120-01-00-S1
END DESCRIPTION:
Bridge Culvert--1,0,-1,-1, 0
Deck Dist Width WeirC Skew NumUp NumDn MinLoCord MaxHiCord MaxSubmerge Is_Ogee
10,34,2.6,0, 42, 42, , , .95, 0, 0,0,,
  3677.9  3767.9  3787.9  3867.9  3887.9  3897.9  3907.9  4017.9  4077.9  4087.9
  4257.9  4297.9  4347.9  4394.9  4417.9  4507.9  4637.9  4667.8  4707.9  4717.9
  4757.9  4777.9  4784.9  4802.1  4908.1  4956.1  4961.4    4964  4999.7 5039.59
  5039.7  5042.1  5068.9  5090.3  5137.9  5175.7  5186.8  5266.8  5276.8  5326.8
  5356.8    5370
    96.6    96.7      97    96.4    96.5    96.2    96.7      97    97.1    96.9
    96.9    97.6    97.6    98.5   98.26    97.3   95.31    94.8   93.85   93.61
   92.81   92.18   92.11   91.72   91.03   91.09   91.59   91.61   91.92   91.82
   91.82   91.36   91.17   91.02   91.08   91.27   91.91    91.8    92.1    91.9
    92.3    93.4
    96.6    96.7      97    96.4    96.5    96.2    96.7      97    97.1    96.9
    96.9    97.6    97.6   97.53    97.5    96.6    95.3    93.6    93.6    93.2
    92.8    92.1    92.1   91.71   90.45   89.88   89.82   89.79   89.92   89.82
   89.69    89.7   89.76   90.05   90.72   91.25    91.9    91.8    92.1    91.9
    92.3    93.4
  3677.9  3767.9  3787.9  3867.9  3887.9  3897.9  3907.9  4017.9  4077.9  4087.9
  4257.9  4297.9  4347.9  4394.9  4417.9  4507.9  4637.9  4667.8  4707.9  4717.9
  4757.9  4777.9  4784.9  4802.1  4908.1  4956.1  4961.4    4964  4999.7 5039.59
  5039.7  5042.1  5068.9  5090.3  5137.9  5175.7  5186.8  5266.8  5276.8  5326.8
  5356.8    5370
    96.6    96.7      97    96.4    96.5    96.2    96.7      97    97.1    96.9
    96.9    97.6    97.6    98.5   98.26    97.3   95.31    94.8   93.85   93.61
   92.81   92.18   92.11   91.72   91.03   91.09   91.59   91.61   91.92   91.82
   91.82   91.36   91.17   91.02   91.08   91.27   91.91    91.8    92.1    91.9
    92.3    93.4
   96.51   96.61   96.91   96.31   96.41   96.11   96.61   96.91   97.01   96.81
   96.81   97.51   97.51   97.44   97.41   96.51   95.21   93.51   93.51   93.11
   92.71   92.01   92.01   91.62   90.36   89.79   89.73    89.7   89.83   89.73
    89.6   89.61   89.67   89.96   90.63   91.16   91.81   91.71   92.01   91.81
   92.21   93.31
Pier Skew, UpSta & Num, DnSta & Num=  ,5001.3, 2 ,5001.3, 2 , 0 , 0 , 0 ,,
     1.3     1.3
   74.83   90.92
     1.3     1.3
   74.74   90.83
BR Coef= 1 , 1 , 1 ,1.25, 0 ,,,.8,0,2,0,
WSPro=,,,, 1 ,,,, 0 ,,,, 0 ,,,,-1 ,-1 ,-1 , 0 , 0 , 0 , 0 , 0
BR U #Sta/Elev= 57
  4017.9      97  4077.9    97.1  4087.9    96.9  4257.9    96.9  4297.9    97.6
  4347.9    97.6  4394.9   97.53  4417.9    97.5  4507.9    96.6  4637.9    95.3
  4667.8    93.6  4667.9    93.6  4707.9    93.6  4717.9    93.2  4757.9    92.8
  4777.9    92.1  4784.9    92.1  4797.9   91.81  4802.1   91.71  4805.5   91.67
  4859.4   91.03  4908.1   90.45  4956.1   89.88  4961.4   89.82 4961.51   89.82
  4961.6   89.82  4961.7   89.82    4964   89.79    4992    77.9  4995.1   76.13
  4995.6    75.8  4999.7   75.83  5000.1   75.83  5004.5   75.85  5004.9   76.14
  5007.2   78.11  5035.4   89.68  5039.5   89.69 5039.59   89.69  5039.7   89.69
  5039.8   89.69  5042.1    89.7  5068.9   89.76  5090.3   90.05  5094.4    90.1
  5137.9   90.72  5161.8   91.05  5162.6   91.06  5175.7   91.25  5186.8    91.9
  5262.7   91.81  5266.8    91.8  5276.8    92.1  5326.8    91.9  5356.8    92.3
  5366.8    93.1    5370    93.4
BR U #Mann= 3
  4017.9      .1    4964     .02  5035.4     .05
BR U Banks=4964,5035.4
BR D #Sta/Elev= 57
  4017.9   96.91  4077.9   97.01  4087.9   96.81  4257.9   96.81  4297.9   97.51
  4347.9   97.51  4394.9   97.44  4417.9   97.41  4507.9   96.51  4637.9   95.21
  4667.8   93.51  4667.9   93.51  4707.9   93.51  4717.9   93.11  4757.9   92.71
  4777.9   92.01  4784.9   92.01  4797.9   91.72  4802.1   91.62  4805.5   91.58
  4859.4   90.94  4908.1   90.36  4956.1   89.79  4961.4   89.73 4961.51   89.73
  4961.6   89.73  4961.7   89.73    4964    89.7    4992   77.81  4995.1   76.04
  4995.6   75.71  4999.7   75.74  5000.1   75.74  5004.5   75.76  5004.9   76.05
  5007.2   78.02  5035.4   89.59  5039.5    89.6 5039.59    89.6  5039.7    89.6
  5039.8    89.6  5042.1   89.61  5068.9   89.67  5090.3   89.96  5094.4   90.01
  5137.9   90.63  5161.8   90.96  5162.6   90.97  5175.7   91.16  5186.8   91.81
  5262.7   91.72  5266.8   91.71  5276.8   92.01  5326.8   91.81  5356.8   92.21
  5366.8   93.01    5370   93.31
BR D #Mann= 3
  4017.9      .1    4964     .02  5035.4     .05
BR D Banks=4964,5035.4
BC Design=,, 0 ,, 0 ,,,,,,
BC HTab HWMax=97.6

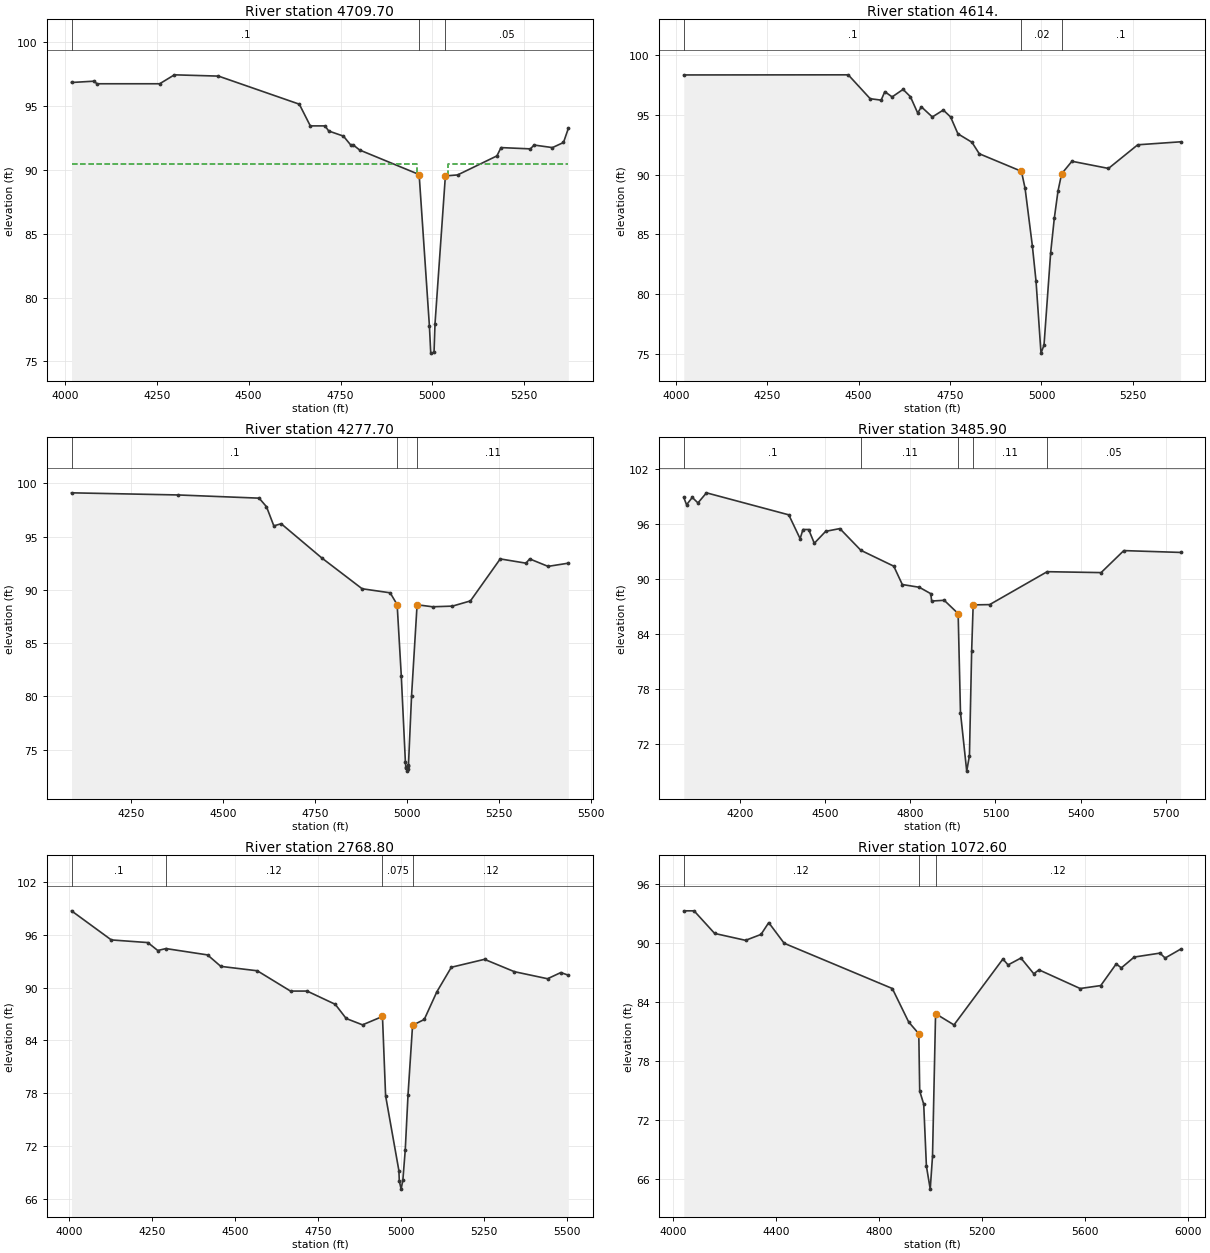
Type RM Length L Ch R = 1 ,4709.70 ,94,95.7,96
BEGIN DESCRIPTION:
EAST NORTH HILL - XS 2
Downstream Section of Bridge/Culvert/Weir
END DESCRIPTION:
XS GIS Cut Line= 5
 3099195.476966213944361.6303224      3098594.13     13943883.28
      3098468.85     13943809.72      3098373.31     13943724.24
      3098072.67     13943623.02
#Sta/Elev= 28
  4017.9   96.85  4077.9   96.95  4087.9   96.75  4257.9   96.75  4297.9   97.45
  4417.9   97.35  4637.9   95.15  4667.8   93.45  4707.9   93.45  4717.9   93.05
  4757.9   92.65  4777.9   91.95  4784.9   91.95  4802.1   91.56    4964   89.64
    4992   77.75  4995.6   75.65  5004.5    75.7  5007.2   77.96  5035.4   89.53
  5068.9   89.61  5175.7    91.1  5186.8   91.75  5266.8   91.65  5276.8   91.95
  5326.8   91.75  5356.8   92.15    5370   93.25
#Mann= 3 ,-1 , 0
  4017.9      .1       0    4964     .02       0  5035.4     .05       0
#XS Ineff= 2 , 0
       0 4957.33    90.5 5042.07       0    90.5
Permanent Ineff=
       F       F
Bank Sta=4964,5035.4
XS Rating Curve= 0
Exp/Cntr=.5,.3

Type RM Length L Ch R = 1 ,4614.   ,350,336.3,324
BEGIN DESCRIPTION:
EAST NORTH HILL - XS 1
END DESCRIPTION:
XS GIS Cut Line= 5
       3099264.1     13944295.96      3098662.75     13943817.64
      3098537.48     13943744.08      3098441.93      13943658.6
      3098141.29     13943557.38
#Sta/Elev= 30
  4021.5   98.36  4471.5   98.37  4531.5   96.37  4561.5   96.25  4571.5   96.96
  4591.5   96.52  4621.5   97.15  4641.5   96.54  4661.5   95.17  4671.5   95.69
  4701.5   94.84  4731.5   95.42  4751.5   94.84  4771.5   93.43  4809.9   92.72
  4829.9   91.76  4945.2   90.29  4955.2   88.87  4975.2   84.03  4985.2   81.08
 4998.77   75.06 5007.01   75.73  5025.2   83.47  5035.2   86.36  5045.2   88.62
  5055.2   90.08  5083.4   91.13  5183.4   90.53  5263.4   92.51  5380.6   92.76
#Mann= 3 ,-1 , 0
  4021.5      .1       0  4945.2     .02       0  5055.2      .1       0
Bank Sta=4945.2,5055.2
XS Rating Curve= 0
Exp/Cntr=.3,.1

Type RM Length L Ch R = 1 ,4277.70 ,757.4,791.8,852.4
BEGIN DESCRIPTION:
Cross Section K120-01-00-X04
END DESCRIPTION:
XS GIS Cut Line= 4
 3099320.199240413944100.1961559      3098760.61     13943484.45
      3098559.34     13943387.68      3098276.78     13943302.53
#Sta/Elev= 28
  4087.9    99.1  4377.9    98.9  4597.9    98.6  4617.9    97.8  4637.9      96
  4657.9    96.2  4767.9      93  4877.9    90.1  4954.1   89.72  4973.1   88.61
  4984.3   81.96  4995.5   73.84  4996.8   73.38  4996.9   73.29  5000.9   72.99
    5003   73.19  5003.3   73.45  5003.9    73.6  5012.3   80.08  5027.3    88.6
  5069.2   88.41  5123.3   88.47  5172.3   88.96  5253.3    92.9  5323.3    92.5
  5333.3    92.9  5383.3    92.2  5438.4    92.5
#Mann= 3 ,-1 , 0
  4087.9      .1       0  4973.1    .075       0  5027.3     .11       0
Bank Sta=4973.1,5027.3
XS Rating Curve= 0
Exp/Cntr=.3,.1

Type RM Length L Ch R = 1 ,3485.90 ,637.47,717.1,749.17
BEGIN DESCRIPTION:
Cross Section K120-01-00-X03
END DESCRIPTION:
XS GIS Cut Line= 4
 3099674.431707913944199.6070441      3099457.32     13943356.72
      3099333.46      13943174.8  3098882.17686313942693.2235033
#Sta/Elev= 30
  4001.8    98.9  4011.8    98.1  4031.8    98.9  4051.8    98.3  4081.8    99.4
  4371.8      97  4411.8    94.4  4421.8    95.4  4441.8    95.4  4461.8    93.9
  4501.8    95.2  4551.8    95.5  4625.9   93.13  4741.8    91.4  4771.8    89.4
  4831.8    89.1  4872.2    88.4  4875.2    87.6  4919.5   87.68  4968.6   86.23
  4976.8   75.43  4998.8   69.05  5008.4   70.74  5016.2   82.17  5021.5   87.18
  5079.6   87.21  5282.3    90.8  5472.3    90.7  5552.3    93.1  5752.3    92.9
#Mann= 5 ,-1 , 0
  4001.8      .1       0  4625.9     .11       0  4968.6    .075       0
  5021.5     .11       0  5282.3     .05       0
Bank Sta=4968.6,5021.5
XS Rating Curve= 0
Exp/Cntr=.3,.1

Type RM Length L Ch R = 1 ,2768.80 ,667.3,1696.2,506.3
BEGIN DESCRIPTION:
Cross Section K120-01-00-X02
END DESCRIPTION:
XS GIS Cut Line= 4
 3099905.834816713944069.0598698      3099948.89     13943275.43
      3100057.27     13942985.14      3099991.47     13942598.07
#Sta/Elev= 30
  4006.8    98.7  4126.8    95.4  4236.8    95.1  4266.8    94.2  4291.4   94.42
  4416.8    93.7  4456.8    92.4  4566.8    91.9  4666.8    89.6  4716.8    89.6
  4801.6    88.1  4834.6   86.49  4883.9   85.77    4944   86.72  4953.4   77.73
  4993.5   69.23  4994.7   68.07  5000.2   67.14  5005.4   68.15  5012.6   71.56
    5021   77.84  5034.7   85.72  5069.9   86.38  5107.8   89.51  5151.5    92.3
  5251.5    93.2  5341.5    91.8  5441.5      91  5481.5    91.7  5504.1    91.4
#Mann= 4 ,-1 , 0
  4006.8      .1       0  4291.4     .12       0    4944    .075       0
  5034.7     .12       0
Bank Sta=4944,5034.7
XS Rating Curve= 0
Exp/Cntr=.3,.1

Type RM Length L Ch R = 1 ,1072.60 ,0,0,0
BEGIN DESCRIPTION:
Cross Section K120-01-00-X01
END DESCRIPTION:
XS GIS Cut Line= 4
      3101555.17     13943446.75      3101404.25     13942586.46
      3101257.17      13942489.7 3100499.566483213942041.9405758
#Sta/Elev= 30
  4042.8    93.3  4082.8    93.3  4162.8      91  4282.8    90.3  4342.8    90.9
  4372.8    92.1  4432.8      90  4852.8    85.4  4916.2      82  4955.6    80.8
  4959.2   74.97  4974.7   73.64  4985.2   67.34    5000      65  5008.9   68.33
  5020.8   82.84  5092.3    81.7  5282.3    88.4  5302.3    87.8  5352.3    88.5
  5402.3    86.9  5422.3    87.3  5582.3    85.4  5662.3    85.7  5722.3    87.9
  5742.3    87.5  5792.3    88.6  5892.3      89  5912.3    88.5  5972.3    89.4
#Mann= 3 ,-1 , 0
  4042.8     .12       0  4955.6    .075       0  5020.8     .12       0
Bank Sta=4955.6,5020.8
XS Rating Curve= 0
Exp/Cntr=.3,.1

Chan Stop Cuts=-1